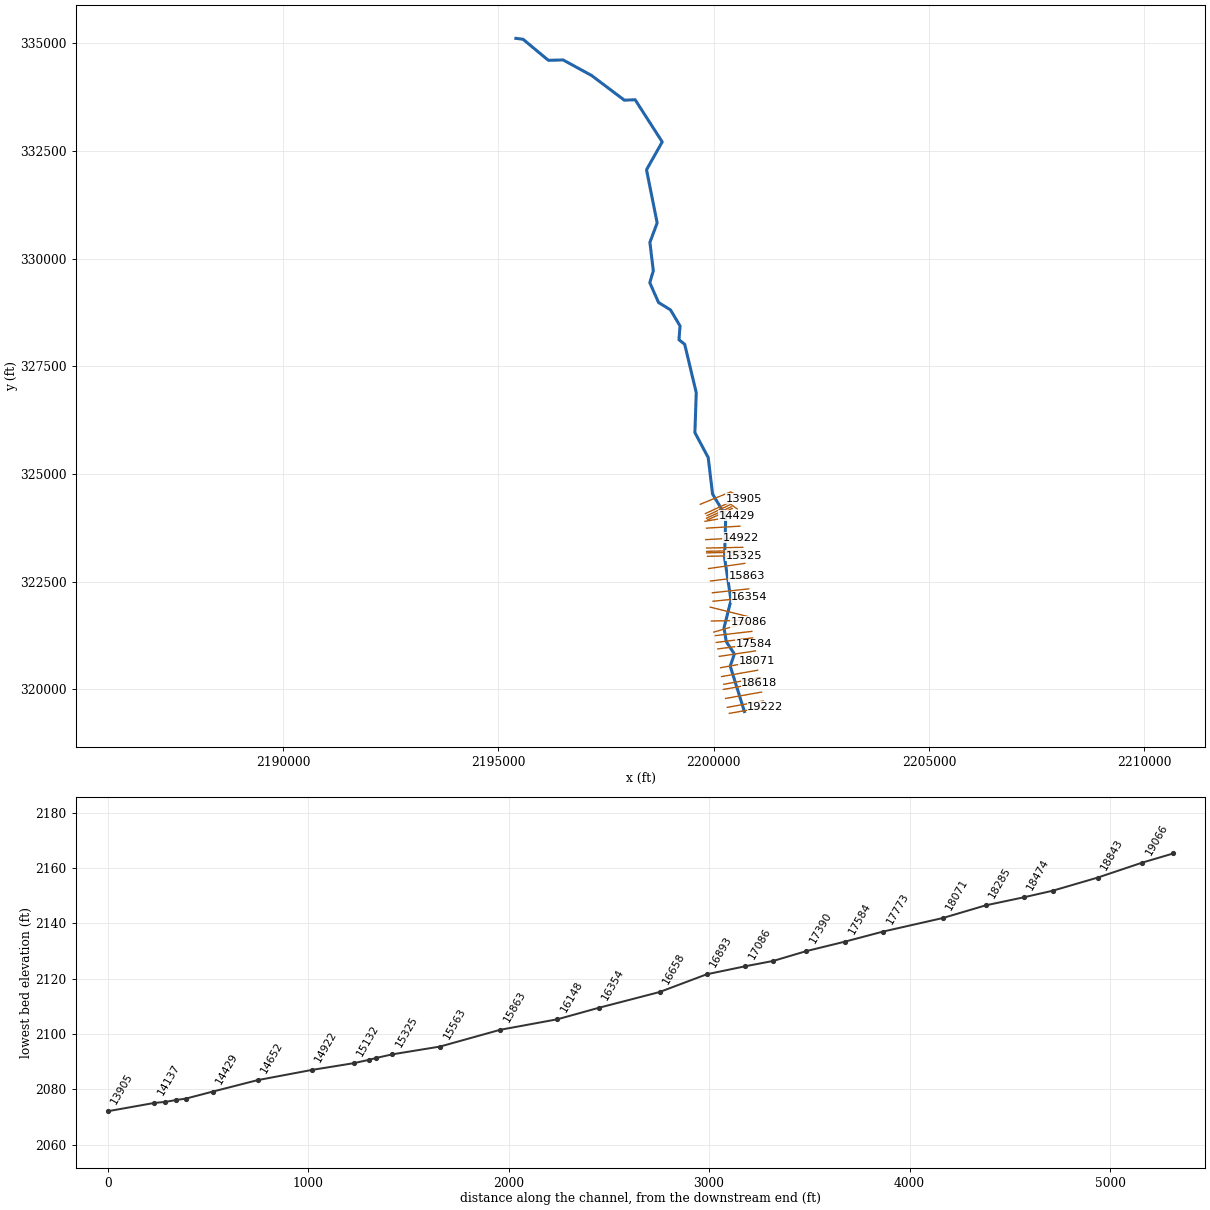
--- ANTNYCKT2.prj (project) ---

Proj Title=ANTNYCKT2
Current Plan=p01
Default Exp/Contr=0.3,0.1
English Units
Geom File=g02
Flow File=f02
Plan File=p01
BEGIN DESCRIPTION:
Stream Name- Anthony Creek Tributary 2
Flood Zone: Zone A
Greenbrier County, WV
County-Wide Study
WVDHSEM-2018-3, Flood Risk Project
HEC-RAS Version: 5.0.7
General Notes:
For the Hydrology regression was used.
END DESCRIPTION:
DSS Export Rating Curves= 0
DSS Export Rating Curve Sorted= 0
DSS Export Volume Flow Curves= 0
DXF OffsetX= 0
DXF OffsetY= 0
DXF ScaleX= 0
DXF ScaleY= 0

--- ANTNYCKT2.p01 (plan) ---

Plan Title=Floodplain
Program Version=5.07
Short Identifier=Floodplain
Geom File=g02
Flow File=f02
Subcritical Flow
K Sum by GR= 0
Std Step Tol= 0.01
Critical Tol= 0.01
Num of Std Step Trials= 20
Max Error Tol= 0.3
Flow Tol Ratio= 0.001
Split Flow NTrial= 30
Split Flow Tol= 0.02
Split Flow Ratio= 0.02
Log Output Level= 0
Friction Slope Method= 1
Unsteady Friction Slope Method= 2
Unsteady Bridges Friction Slope Method= 1
Parabolic Critical Depth
Global Vel Dist= 0 , 0 , 0
Global Log Level= 0
CheckData=True
Encroach Param=-1 ,0,0, 0
Mapping Interval=1HOUR
Computation Time Step Use Courant=        0
Computation Time Step Use Time Series=    0
Computation Time Step Count To Double=0
Computation Time Step Max Doubling=0
Computation Time Step Max Halving=0
Computation Time Step Residence Courant=0
Run HTab= 0
Run UNet= 0
Run Sediment= 0
Run PostProcess= 0
Run WQNet= 0
Run RASMapper=-1
UNET Theta= 0
UNET Theta Warmup= 0
UNET ZTol= 0
UNET ZSATol= 0
UNET MxIter= 0
UNET Max Iter WO Improvement= 0
UNET MaxInSteps= 0
UNET DtIC= 0
UNET DtMin= 0
UNET MaxCRTS= 0
UNET WFStab= 0
UNET SFStab= 0
UNET WFX= 1
UNET SFX= 1
UNET 1D Methodology=Finite Difference
UNET DSS MLevel= 1
UNET Pardiso=0
UNET DZMax Abort= 0
UNET Use Existing IB Tables= 0
UNET Froude Reduction=False
UNET Froude Limit= 0
UNET Froude Power= 0
UNET D1 Cores= 0
UNET D2 Coriolis=0
UNET D2 Cores= 0
UNET D2 Theta= 1
UNET D2 Theta Warmup= 1
UNET D2 Z Tol= 0.01
UNET D2 Volume Tol= 0.01
UNET D2 Max Iterations= 20
UNET D2 Equation= 0
UNET D2 RampUpFraction=0.1
UNET D2 TimeSlices= 1
UNET D2 BCVolumeCheck=0
UNET D1D2 MaxIter= 0
UNET D1D2 ZTol=0.01
UNET D1D2 QTol=0.1
UNET D1D2 MinQTol=1
Write IC File= 0
Write IC File at Fixed DateTime=0
Write IC File at Sim End=0
Echo Input=False
Echo Parameters=False
Echo Output=False
Write Detailed= 0
HDF Write Warmup=0
HDF Write Time Slices=0
HDF Flush=0
HDF Face Node Velocities=0
HDF Compression= 1
HDF Chunk Size= 1
HDF Spatial Parts= 1
HDF Use Max Rows=0
HDF Fixed Rows= 1
Calibration Method= 0
Calibration Iterations= 20
Calibration Max Change=0.05
Calibration Tolerance=0.2
Calibration Maximum=1.5
Calibration Minimum=0.5
Calibration Optimization Method= 1
WQ AD Non Conservative
WQ ULTIMATE=-1
WQ Max Comp Step=1HOUR
WQ Output Interval=15MIN
WQ Output Selected Increments= 0
WQ Output face flow=0
WQ Output face velocity=0
WQ Output face area=0
WQ Output face dispersion=0
WQ Output cell volume=0
WQ Output cell surface area=0
WQ Output cell continuity=0
WQ Output cumulative cell continuity=0
WQ Output face conc=0
WQ Output face dconc_dx=0
WQ Output face courant=0
WQ Output face peclet=0
WQ Output face adv mass=0
WQ Output face disp mass=0
WQ Output cell mass=0
WQ Output cell source sink temp=0
WQ Output nsm pathways=0
WQ Output nsm derived pathways=0
WQ Output MaxMinRange=-1
WQ Daily Max Min Mean=-1
WQ Daily Range=0
WQ Daily Time=0
WQ Create Restart=0
WQ Fixed Restart=0
WQ System Summary=0
WQ Write To DSS=0
WQ Use Fixed Temperature=0
Sorting and Armoring Iterations= 10
XS Update Threshold= 0.02
Bed Roughness Predictor= 0
Hydraulics Update Threshold= 0.02
Energy Slope Method= 1
Volume Change Method= 1
Sediment Retention Method= 0
XS Weighting Method= 0
Number of US Weighted Cross Sections= 1
Number of DS Weighted Cross Sections= 1
Upstream XS Weight=0
Main XS Weight=1
Downstream XS Weight=0
Number of DS XS's Weighted with US Boundary= 1
Upstream Boundary Weight= 1
Weight of XSs Associated with US Boundary= 0
Number of US XS's Weighted with DS Boundary= 1
Downstream Boundary Weight= 0.5
Weight of XSs Associated with DS Boundary= 0.5
Percentile Method= 0
Sediment Output Level= 3
Mass or Volume Output= 0
Output Increment Type= 1
Profile and TS Output Increment= 1
XS Output Flag= 0
XS Output Increment= 10
Write Gradation File= 0
Read Gradation Hotstart= 0
Write HDF5 File= 1
Write Binary Output= 1
Write DSS Sediment File= 0
SV Curve= 0
Specific Gage Flag= 0

--- ANTNYCKT2.f02 (steady flow) ---

Flow Title=ANTNYCKT2
Program Version=5.07
Number of Profiles= 6
Profile Names=f1p,f10p,f4p,f2p,f02p,f1pplus
River Rch & RM=ANTNYCKT2,Main            ,19222
     392     204     274     331     552     580
River Rch & RM=ANTNYCKT2,Main            ,18474
     627     333     442     532     875     928
River Rch & RM=ANTNYCKT2,Main            ,15863
     699     372     493     593     973    1030
River Rch & RM=ANTNYCKT2,Main            ,10845
    1250     681     892    1070    1720    1850
River Rch & RM=ANTNYCKT2,Main            ,4604
    1430     783    1020    1220    1960    2110
Boundary for River Rch & Prof#=ANTNYCKT2,Main            , 1
Up Type= 0
Dn Type= 3
Dn Slope=0.007
Boundary for River Rch & Prof#=ANTNYCKT2,Main            , 2
Up Type= 0
Dn Type= 3
Dn Slope=0.007
Boundary for River Rch & Prof#=ANTNYCKT2,Main            , 3
Up Type= 0
Dn Type= 3
Dn Slope=0.007
Boundary for River Rch & Prof#=ANTNYCKT2,Main            , 4
Up Type= 0
Dn Type= 3
Dn Slope=0.007
Boundary for River Rch & Prof#=ANTNYCKT2,Main            , 5
Up Type= 0
Dn Type= 3
Dn Slope=0.007
Boundary for River Rch & Prof#=ANTNYCKT2,Main            , 6
Up Type= 0
Dn Type= 3
Dn Slope=0.007
DSS Import GetInterval= 0
DSS Import GetPeak= 0
DSS Import FillOption= 0

--- ANTNYCKT2.g02 (geometry) ---

Geom Title=ANTNYCKT2
Program Version=5.07

River Reach=ANTNYCKT2       ,Main
Reach XY= 30
2200716.12899999319480.1500000212200386.36900003320536.511000007
2200483.16800003320816.9580000192200294.25500001321105.361000016
2200241.75200002321424.2240000222200404.54200001322066.548999995
2200255.35700001323049.8970000152200282.19800003 324019.56400001
2199976.41900004324532.1950000082199874.97399999325379.996000022
2199566.17000003325957.6590000092199597.61499999326886.127000004
2199329.27800001328008.481000006     2199195.862328116.591000006
2199222.03000002328433.6130000052198998.78199999328809.311000004
2198722.45600002328978.3199999932198518.98500003329438.555999994
2198600.45800002329716.9660000212198521.01000004330375.950000018
2198689.62100004330827.952000007     2198442.353      332061.309
2198807.60900001332709.1870000212198178.37800001333688.171000019
2197927.68500002333678.2800000012197169.11600004334250.239000008
     2196505.957334612.3910000182196163.83900003334603.607000008
2195575.95400004 335091.939000012195408.59268938335114.206146643

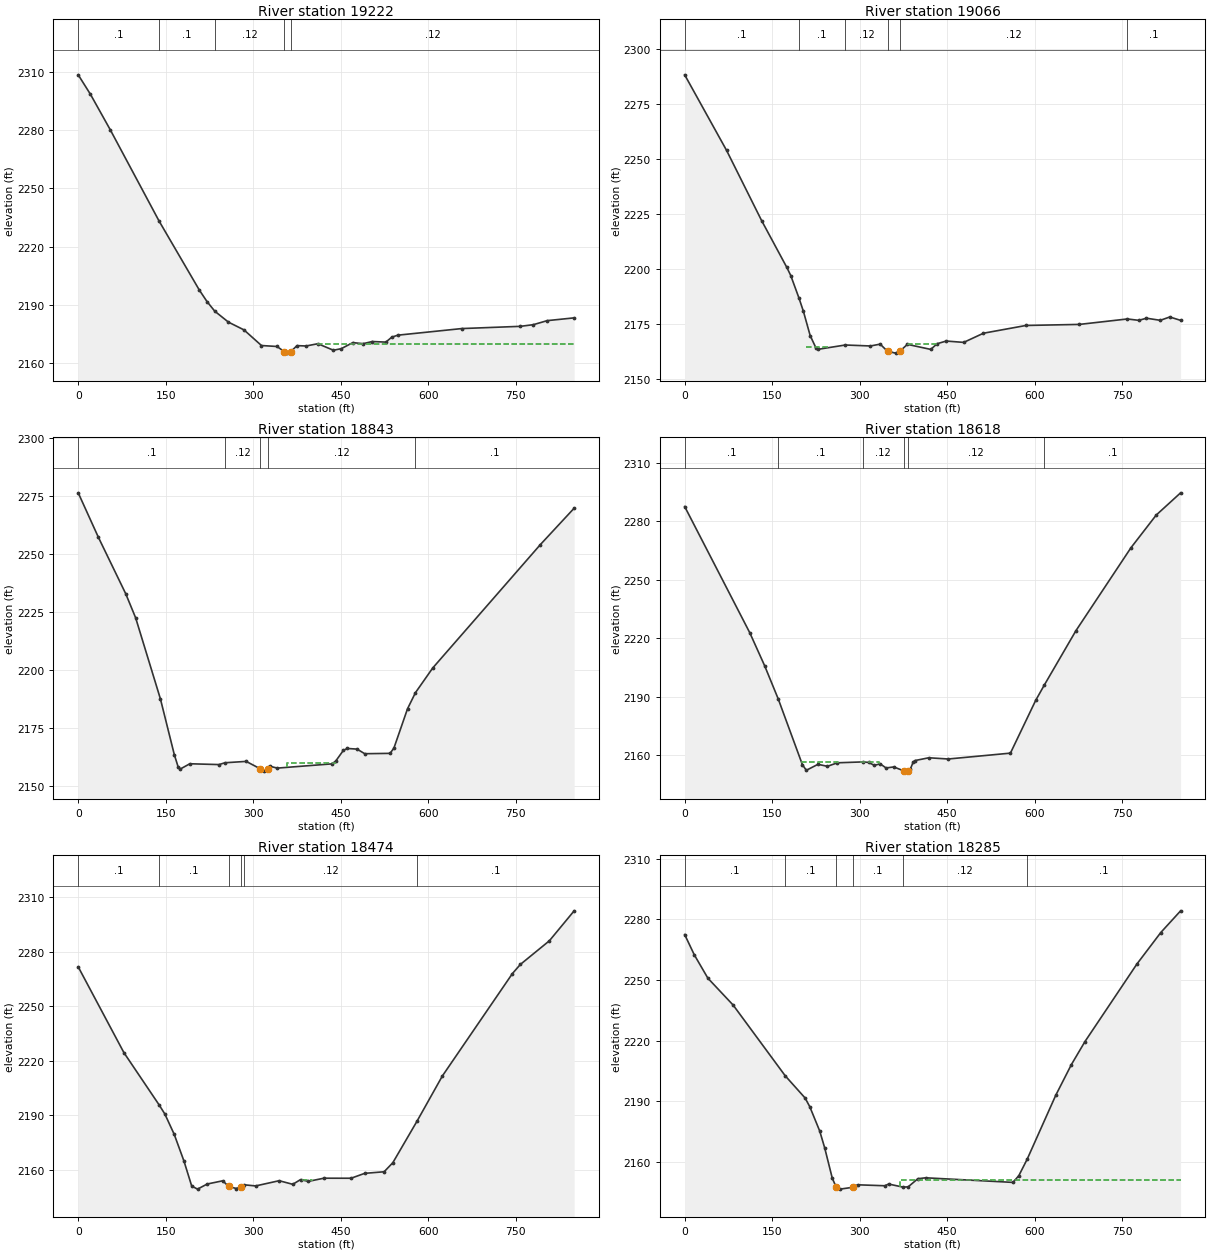
Type RM Length L Ch R = 1 ,19222   ,155.4,155.4,155.4
XS GIS Cut Line= 2
2200364.98008826319438.0084285782201202.06359083319585.626888573
#Sta/Elev= 30
       0 2308.51      21 2298.47      55 2280.19  138.572233.266   207.5 2197.76
   220.8 2191.78  234.082186.838   257.5 2181.21   284.1 2177.22   314.1 2169.17
   340.8 2168.68   353.42165.959   357.4 2165.26   364.1 2165.99     375 2169.11
   390.7 2168.94   410.7  2170.1   437.4 2166.75   450.7 2167.54   470.7 2170.67
   488.3 2170.13     504 2171.23   527.3 2170.93   537.3 2173.45   547.7  2174.5
   657.3  2177.9   757.8 2179.05     780  2179.9   803.8 2181.98     850 2183.41
#Mann= 5 ,-1 , 0
       0      .1       0  138.57      .1       0  234.08     .12       0
   353.4    .045       0   364.1     .12       0
#XS Ineff= 2 , 0
                           409.9         2170.08
Permanent Ineff=
       F       F
Bank Sta=353.4,364.1
XS Rating Curve= 0 ,0
Exp/Cntr(USF)=0,0
Exp/Cntr=0.3,0.1

Type RM Length L Ch R = 1 ,19066   ,223.2,223.2,223.2
XS GIS Cut Line= 2
2200318.11807475319578.5944691312201155.20157732319726.212929126
#Sta/Elev= 30
       0 2288.42    71.9 2254.03   131.8  2222.2   175.1 2200.88   181.8 2197.21
  195.942186.928   203.5 2180.93   215.1  2169.9   225.1 2164.25   228.5 2163.67
  275.322165.632   318.4 2165.19   335.1 2166.03   347.72162.744   361.7 2161.94
   368.4  2162.7   381.7 2165.93   421.7 2163.63   432.8 2166.23   448.3 2167.43
   478.2 2166.82   512.1 2170.99   584.9 2174.51   676.4 2174.99   758.72177.464
   778.3 2176.84   791.5 2177.81   815.2 2176.85   831.4 2178.37     850 2176.83
#Mann= 6 ,-1 , 0
       0      .1       0  195.94      .1       0  275.32     .12       0
   347.7    .045       0   368.4     .12       0   758.7      .1       0
#XS Ineff= 2 ,-1
  207.85  248.032164.941  383.08  435.38 2165.95
Permanent Ineff=
       F       F
Bank Sta=347.7,368.4
XS Rating Curve= 0 ,0
Exp/Cntr(USF)=0,0
Exp/Cntr=0.3,0.1

Type RM Length L Ch R = 1 ,18843   ,224.7,224.7,224.7
XS GIS Cut Line= 2
 2200279.2349328319785.1180386552201116.31843537319932.736498651
#Sta/Elev= 30
       0 2276.34    34.7 2257.12    81.4 2232.91    98.4 2222.54   140.9  2187.6
   164.7 2163.62   171.3 2158.29   174.7 2157.38   191.3 2159.68   241.3 2159.33
  251.662160.118   287.9  2160.7   311.42157.594   317.9 2156.51   324.9 2157.56
   327.9 2158.65   341.2 2157.81   434.5 2159.63   441.2 2160.79   454.5 2165.45
   461.2 2166.27   477.9 2165.99   491.1 2164.01   534.5 2164.16   541.1 2166.44
   564.4 2183.35  578.022190.303   607.7 2200.95   792.2 2254.08     850 2269.72
#Mann= 5 ,-1 , 0
       0      .1       0  251.66     .12       0   311.4    .045       0
   324.9     .12       0  578.02      .1       0
#XS Ineff= 2 ,-1
  165.59  249.062159.876  358.03  440.972159.931
Permanent Ineff=
       F       F
Bank Sta=311.4,324.9
XS Rating Curve= 0 ,0
Exp/Cntr(USF)=0,0
Exp/Cntr=0.3,0.1

Type RM Length L Ch R = 1 ,18618   ,144.2,144.2,144.2
XS GIS Cut Line= 2
2200226.21332783 319993.47936442 2201063.2968304320141.097824416
#Sta/Elev= 30
       0 2287.64   111.6 2222.81   137.1 2205.85   160.32188.863   201.8 2155.05
   208.5 2152.19   228.5 2155.26   244.7 2154.23   261.8 2156.04  305.372156.496
   315.1 2156.24   325.1 2154.74   335.1 2155.51   345.1 2153.39   358.4 2153.91
   375.1 2151.95   380.6 2151.76   383.4 2151.91  386.48 2152.61   391.7 2156.42
   395.1 2157.21   418.4 2158.62   451.7 2157.99   558.3    2161   601.6 2188.09
  616.362195.955   670.5 2223.85   764.9 2266.49   808.2 2283.27     850 2294.68
#Mann= 6 ,-1 , 0
       0      .1       0   160.3      .1       0  305.37     .12       0
   375.1    .045       0   383.4     .12       0  616.36      .1       0
#XS Ineff= 2 ,-1
  198.96  262.612156.356   299.7  333.072156.417
Permanent Ineff=
       F       F
Bank Sta=375.1,383.4
XS Rating Curve= 0 ,0
Exp/Cntr(USF)=0,0
Exp/Cntr=0.3,0.1

Type RM Length L Ch R = 1 ,18474   ,188.9,188.9,188.9
XS GIS Cut Line= 2
2200236.74702059320114.2037973812201073.83052315320261.822257377
#Sta/Elev= 30
       0 2271.64    78.3 2224.47  138.262195.911   148.4 2190.77   164.5 2179.56
   181.2 2164.87   194.5 2151.09   204.5 2149.39   221.1  2152.2   247.8 2153.98
   257.8 2150.84   271.1 2149.73   278.6 2150.76  284.58 2151.76   304.1 2151.15
   344.4 2154.02   367.7 2152.04     381 2154.62   394.4 2153.65     421  2155.4
   467.7 2155.38     491 2158.07   524.3 2158.94   539.2 2163.91  580.572186.698
   624.2 2211.66   744.2 2267.96   757.8 2272.97   807.5 2285.97     850 2302.46
#Mann= 6 ,-1 , 0
       0      .1       0  138.26      .1       0   257.8    .045       0
   278.6      .1       0  284.58     .12       0  580.57      .1       0
#XS Ineff= 3 ,-1
  188.24  246.382153.643  341.92  378.852153.693  384.27  400.96 2154.38
Permanent Ineff=
       F       F       F
Bank Sta=257.8,278.6
XS Rating Curve= 0 ,0
Exp/Cntr(USF)=0,0
Exp/Cntr=0.3,0.1

Type RM Length L Ch R = 1 ,18285   ,214.4,214.4,214.4
XS GIS Cut Line= 2
  2200185.650597320292.2171440782201022.73409956320439.835604074
#Sta/Elev= 30
       0  2272.4    16.5 2262.36    39.8  2250.8    83.1 2237.51  172.312202.552
   206.4 2191.56   214.4 2187.27   231.4 2175.27   239.9 2166.98     253 2151.88
   259.7 2147.47   266.3  2146.5     288  2147.4     288 2147.41   296.3 2148.64
     343 2148.17   349.6 2149.01  374.042147.508     383 2147.61   399.6 2151.64
   412.9  2152.1   562.7 2149.83   572.8 2153.22  587.082161.343   636.1 2192.98
   662.8  2208.1   686.1  2219.5   775.1 2257.83     816  2273.4     850 2284.13
#Mann= 6 ,-1 , 0
       0      .1       0  172.31      .1       0   259.7    .045       0
     288      .1       0  374.04     .12       0  587.08      .1       0
#XS Ineff= 2 , 0
                          369.35         2150.92
Permanent Ineff=
       F       F
Bank Sta=259.7,288
XS Rating Curve= 0 ,0
Exp/Cntr(USF)=0,0
Exp/Cntr=0.3,0.1

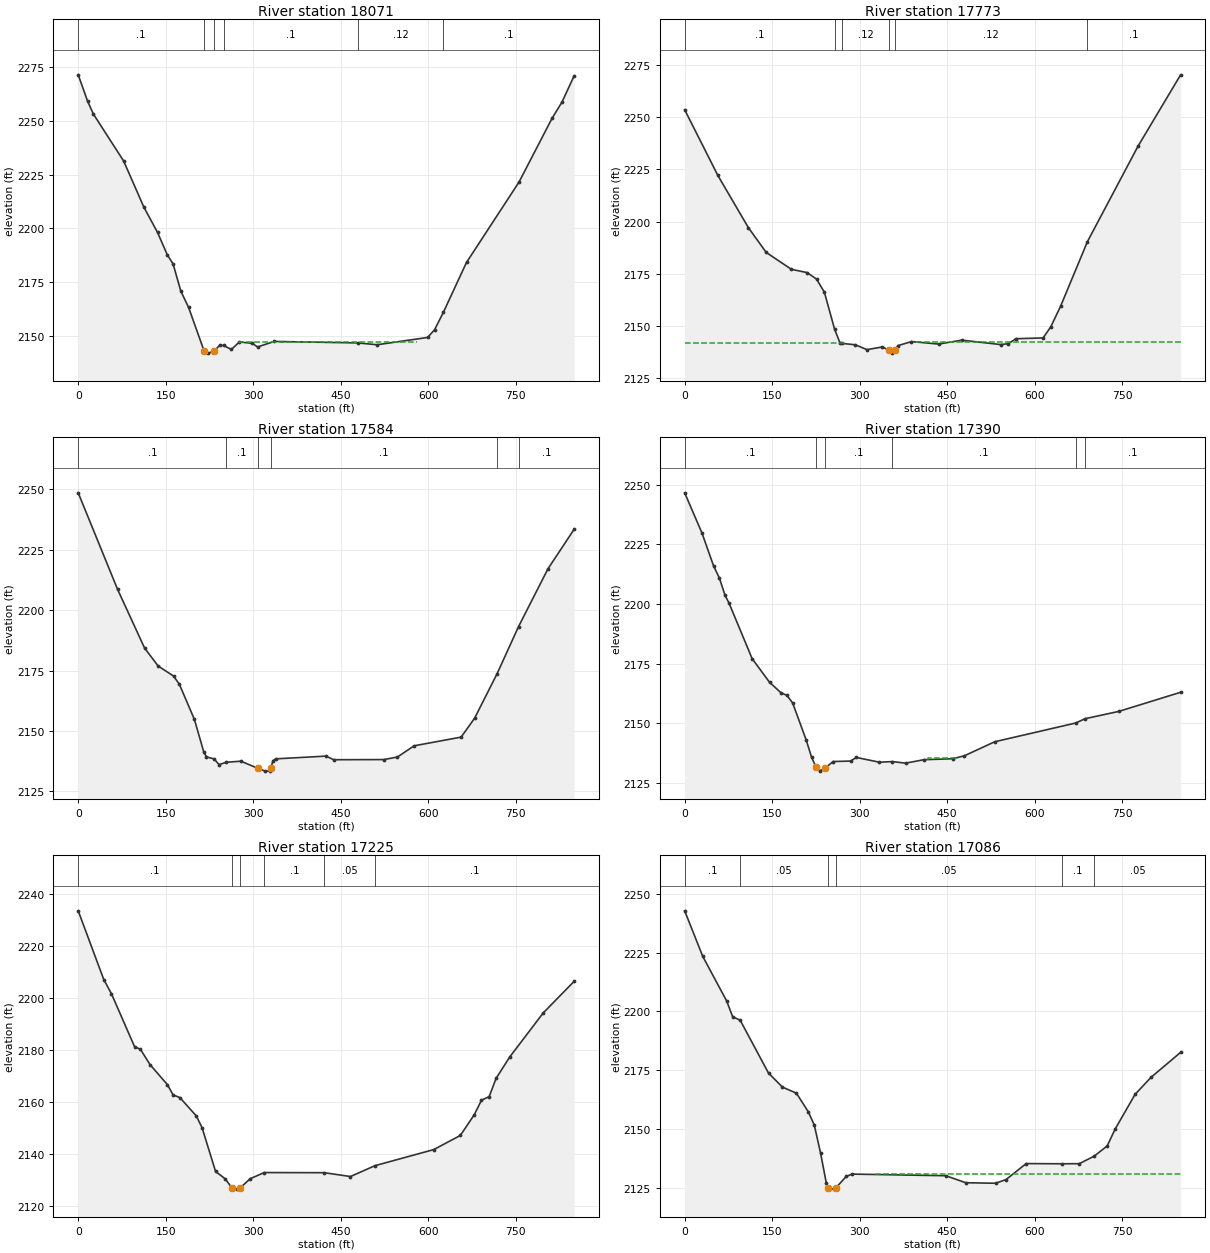
Type RM Length L Ch R = 1 ,18071   ,297.5,297.5,297.5
XS GIS Cut Line= 2
2200163.12642737320499.1777594652201000.39478555320645.744114389
#Sta/Elev= 30
       0 2271.38      16 2259.18      26 2253.14    77.9 2231.26   112.6 2209.78
   135.9  2198.1   152.6 2187.68   162.6  2183.4   175.9 2170.73   189.2 2163.17
   215.9 2142.81   222.5 2141.91   232.5 2142.75   242.5 2145.58  249.022145.461
   262.5 2143.63   276.3 2147.11   298.1 2146.47   307.5  2144.8   336.2 2147.35
  478.852146.658   512.3 2145.81   598.9  2149.2   610.8 2152.79  626.022160.986
   665.5  2184.1   755.5 2221.49     812 2251.09   829.1 2258.66     850 2270.94
#Mann= 6 ,-1 , 0
       0      .1       0   215.9    .045       0   232.5      .1       0
  249.02      .1       0  478.85     .12       0  626.02      .1       0
#XS Ineff= 1 ,-1
  274.93  581.04 2147.14
Permanent Ineff=
       F
Bank Sta=215.9,232.5
XS Rating Curve= 0 ,0
Exp/Cntr(USF)=0,0
Exp/Cntr=0.3,0.1

Type RM Length L Ch R = 1 ,17773   ,189.1,189.1,189.1
XS GIS Cut Line= 2
2200132.51774806320761.4718964152200972.95380738320888.622319948
#Sta/Elev= 30
       0 2253.53    56.9 2222.06   109.1 2197.12   139.8 2185.22     183 2177.13
     210 2175.58   226.1 2172.42   239.4 2166.22   256.92148.522   265.9 2142.09
  270.072141.671   292.5 2141.03   312.4  2138.7   338.9    2140   349.6 2138.48
   355.5 2137.03   360.52138.315   365.6 2140.62   388.7 2142.56   435.2 2141.36
     475 2143.24   541.5 2141.13   554.6 2141.53   567.9 2143.93   614.3  2144.3
   627.6 2149.69   644.2 2159.43  690.242190.374   776.9 2236.04     850 2270.24
#Mann= 6 ,-1 , 0
       0      .1       0   256.9      .1       0  270.07     .12       0
   349.6    .045       0   360.5     .12       0  690.24      .1       0
#XS Ineff= 2 , 0
          276.67  2141.9  396.49         2142.59
Permanent Ineff=
       F       F
Bank Sta=349.6,360.5
XS Rating Curve= 0 ,0
Exp/Cntr(USF)=0,0
Exp/Cntr=0.3,0.1

Type RM Length L Ch R = 1 ,17584   ,193.9,193.9,193.9
XS GIS Cut Line= 2
2200095.53868973320934.8120964132200938.69703441321042.441115762
#Sta/Elev= 30
       0 2248.44    67.5 2208.52   113.8 2184.26     137 2176.86   163.4  2172.7
   173.4  2169.3   199.2 2154.75     215 2141.51   219.7  2139.3   232.9 2138.47
   241.4 2136.11  253.992137.073   278.8 2137.52     308 2134.56   320.5 2133.41
   328.8 2133.51   330.12134.767   333.9 2137.74   338.7 2138.49   424.7 2139.62
   437.9 2138.12     524 2138.19   547.1 2139.24   575.8 2143.88   656.3 2147.47
   679.4 2155.29  718.082173.755  754.732193.175   805.1 2217.03     850 2233.39
#Mann= 6 ,-1 , 0
       0      .1       0  253.99      .1       0     308    .045       0
   330.1      .1       0  718.08     .12       0  754.73      .1       0
#XS Ineff= 2 , 0
          251.18 2136.85  339.67         2138.46
Permanent Ineff=
       F       F
Bank Sta=308,330.1
XS Rating Curve= 0 ,0
Exp/Cntr(USF)=0,0
Exp/Cntr=0.3,0.1

Type RM Length L Ch R = 1 ,17390   ,165.2,165.2,165.2
XS GIS Cut Line= 2
2200064.22152688321084.8048237222200907.37987156321192.433843071
#Sta/Elev= 30
       0 2246.58    29.6 2229.76    49.5 2215.98    59.4 2210.92    69.3 2203.56
    75.9 2200.43   115.6 2177.11   145.4 2167.21   165.2 2162.78   175.2 2161.72
   185.1 2158.51   208.2 2143.05   217.4 2135.89   224.92131.684   231.4 2129.97
   241.3  2131.4   254.5 2133.99   284.3 2134.19   294.2  2135.7   333.9  2133.7
   356.12133.963   378.7 2133.31     410 2134.76   459.6 2135.16   479.5 2136.41
   531.3 2142.27  670.192150.131  686.232151.933   744.1    2155     850 2163.01
#Mann= 6 ,-1 , 0
       0      .1       0   224.9    .045       0   241.3      .1       0
   356.1      .1       0  670.19     .05       0  686.23      .1       0
#XS Ineff= 2 ,-1
   311.3   412.52134.456   417.8  464.95 2135.41
Permanent Ineff=
       F       F
Bank Sta=224.9,241.3
XS Rating Curve= 0 ,0
Exp/Cntr(USF)=0,0
Exp/Cntr=0.3,0.1

Type RM Length L Ch R = 1 ,17225   ,138.9,138.9,138.9
XS GIS Cut Line= 2
2200043.53374865321243.8431776272200887.82957875 321342.15162722
#Sta/Elev= 30
       0 2233.62    43.8 2207.16      57 2201.65    96.7 2181.24   106.6  2180.3
   123.1 2174.39   152.8 2166.68   162.7  2162.7   174.1 2161.71   202.4 2154.63
   212.3 2150.07   235.4 2133.24   251.9 2130.39   263.42126.919   271.7 2126.42
   277.4 2126.87   294.8 2130.43  318.712132.802  421.972132.748   466.6 2131.27
  508.482135.445   609.3 2141.65   654.9 2147.09   678.8 2155.08   691.2 2160.67
   704.4 2162.07   716.1 2169.04   739.5  2177.3   796.9 2194.26     850 2206.47
#Mann= 6 ,-1 , 0
       0      .1       0   263.4    .045       0   277.4      .1       0
  318.71      .1       0  421.97     .05       0  508.48      .1       0
Bank Sta=263.4,277.4
XS Rating Curve= 0 ,0
Exp/Cntr(USF)=0,0
Exp/Cntr=0.3,0.1

Type RM Length L Ch R = 1 ,17086   ,193.2,193.2,193.2
XS GIS Cut Line= 2
 2200004.7311788321325.7719425972200821.53398583321561.001988341
#Sta/Elev= 30
       0 2242.74      31 2223.37      72 2204.42    82.3 2197.71   95.042196.299
   143.7 2173.79   167.6 2167.84   191.5 2165.27     212  2157.3   222.2 2151.66
   232.8 2139.94   242.7 2127.15     246 2125.03   256.4  2124.5   259.3 2125.09
   276.9 2129.89   287.1 2130.89   447.6 2130.19   481.7 2127.22   532.9    2127
   550.9 2128.58   585.3 2135.35  645.85 2135.27   676.3 2135.31  701.912138.521
   724.1 2142.84   737.8 2150.03   771.9 2164.75   799.2 2171.98     850 2182.61
#Mann= 6 ,-1 , 0
       0      .1       0   95.04     .05       0     246    .045       0
   259.3     .05       0  645.85      .1       0  701.91     .05       0
#XS Ineff= 2 , 0
                          327.73            2131
Permanent Ineff=
       F       F
Bank Sta=246,259.3
XS Rating Curve= 0 ,0
Exp/Cntr(USF)=0,0
Exp/Cntr=0.3,0.1

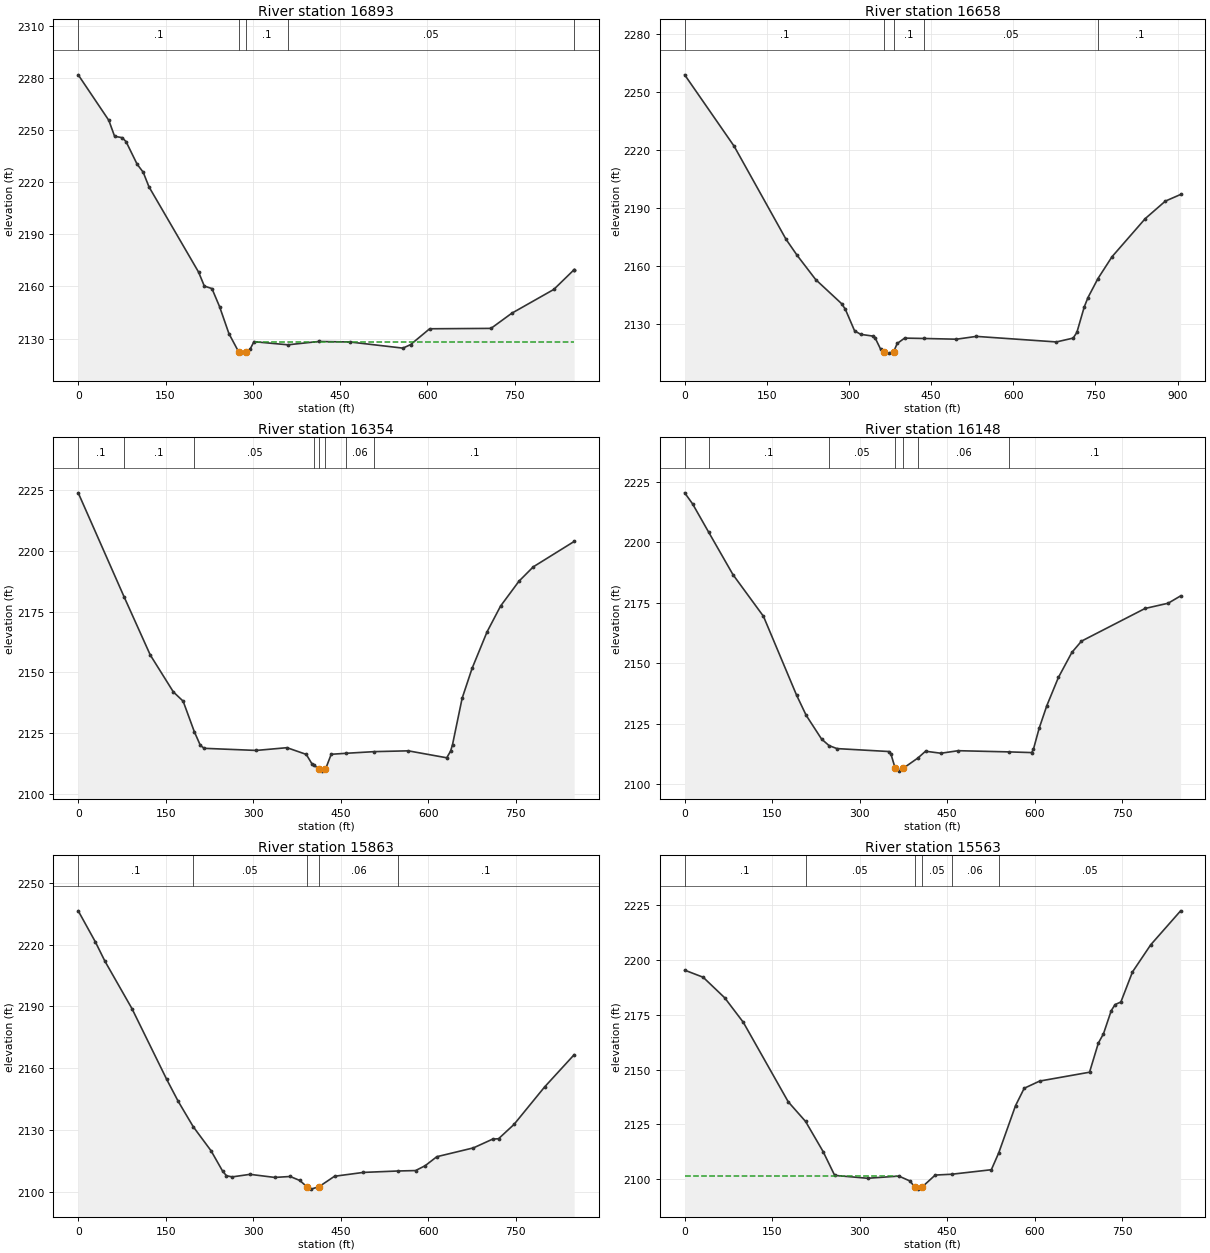
Type RM Length L Ch R = 1 ,16893   ,235.1,235.1,235.1
XS GIS Cut Line= 2
2199949.12505159321583.3046465762200801.25834977321595.502510087
#Sta/Elev= 30
       0  2281.8    52.6 2255.59    62.5 2246.42    75.6 2245.62    82.2 2243.35
   101.2 2230.36   111.7 2225.72   121.5 2217.38   206.9 2168.19   216.7 2160.19
   229.8 2158.75   242.9 2148.35     259 2132.81   275.8 2122.25   275.8 2122.23
     279 2121.59   288.9 2122.25   295.4 2123.88     302 2128.18  360.32 2126.38
   413.6  2128.3   466.7 2128.01   557.9 2124.47   571.1 2126.48   603.9 2135.61
   709.3 2135.83     745 2144.55   817.2 2158.25   851.42169.395   852.2  2169.6
#Mann= 5 ,-1 , 0
       0      .1       0   275.8    .045       0   288.9      .1       0
  360.32     .05       0   851.4      .1       0
#XS Ineff= 2 , 0
                          303.37         2128.18
Permanent Ineff=
       F       F
Bank Sta=275.8,288.9
XS Rating Curve= 0 ,0
Exp/Cntr(USF)=0,0
Exp/Cntr=0.3,0.1

Type RM Length L Ch R = 1 ,16658   ,303.9,303.9,303.9
XS GIS Cut Line= 2
2199920.66337006321905.8703705392200799.06282986321686.308827337
#Sta/Elev= 30
       0  2258.7    90.4 2221.84     185  2173.9   205.3 2165.61   239.2  2153.1
   286.5 2140.69   293.3  2137.8   310.2 2126.68   321.4 2124.86     344 2123.95
   347.4 2123.21   357.5 2117.32   364.7  2115.9   372.5 2115.18   381.6    2116
     388 2120.15   401.5 2122.92   436.12122.743   496.2 2122.36   532.5 2123.81
   678.6 2120.95   709.2 2122.93     716 2125.87   729.5 2139.03   736.3 2143.86
  754.472153.627   780.2 2164.91   840.9 2184.57   877.5 2193.57   905.4    2197
#Mann= 5 ,-1 , 0
       0      .1       0   364.7    .045       0   381.6      .1       0
   436.1     .05       0  754.47      .1       0
Bank Sta=364.7,381.6
XS Rating Curve= 0 ,0
Exp/Cntr(USF)=0,0
Exp/Cntr=0.3,0.1

Type RM Length L Ch R = 1 ,16354   ,205.8,205.8,205.8
XS GIS Cut Line= 2
2199987.16443953322041.1228213612200832.50907493322129.962268693
#Sta/Elev= 30
       0  2223.8   78.762181.009   123.5 2157.18   163.1    2142   179.8 2138.22
  198.892125.738   209.3 2120.06   215.9 2118.84   305.1 2117.97   357.8  2119.1
   390.8 2116.35   400.6 2112.48  404.762111.899   412.4  2110.2   417.1 2109.47
   423.7 2110.19   433.6 2116.39  459.252116.801   507.72117.482   565.6 2117.81
   631.6 2114.95   638.2 2117.67   641.5 2120.33     658 2139.39     675 2151.65
   700.8 2166.72   723.9 2177.29   755.6 2187.55     780  2193.4     850 2203.82
#Mann= 8 ,-1 , 0
       0      .1       0   78.76      .1       0  198.89     .05       0
  404.76    .055       0   412.4    .045       0   423.7    .055       0
  459.25     .06       0   507.7      .1       0
Bank Sta=412.4,423.7
XS Rating Curve= 0 ,0
Exp/Cntr(USF)=0,0
Exp/Cntr=0.3,0.1

Type RM Length L Ch R = 1 ,16148   ,285.5,285.5,285.5
XS GIS Cut Line= 2
2199971.92975837322238.1347747132200816.96835676 322329.83955773
#Sta/Elev= 30
       0 2220.46    13.5 2215.91   41.342204.086    82.8 2186.61     135 2169.39
   191.7 2136.82   208.2 2128.44   234.6 2118.62   247.42115.903     261 2114.66
   350.1 2113.45   353.5 2112.42   360.8 2106.51   366.6 2105.34   374.3 2106.47
  399.63 2110.75   412.8 2113.57   439.2 2112.74   468.9 2113.79   556.52113.292
   594.6 2113.01   597.7 2114.35   607.5 2123.04   620.7 2132.43   640.5 2144.07
   663.6 2154.44   680.1 2159.11     789 2172.62   828.6 2174.79     850 2177.83
#Mann= 7 ,-1 , 0
       0      .1       0   41.34      .1       0   247.4     .05       0
   360.8    .045       0   374.3     .05       0  399.63     .06       0
   556.5      .1       0
Bank Sta=360.8,374.3
XS Rating Curve= 0 ,0
Exp/Cntr(USF)=0,0
Exp/Cntr=0.3,0.1

Type RM Length L Ch R = 1 ,15863   ,299.7,299.7,299.7
XS GIS Cut Line= 2
 2199926.8064312322511.1776413322200770.10238836322617.723071221
#Sta/Elev= 30
       0 2236.32    29.3 2221.32    45.8 2211.92    92.1 2188.97   151.6 2154.73
   171.4 2144.05  197.192131.747   227.7 2120.11   247.4 2110.31   254.1 2108.01
     264 2107.47   294.4  2108.7   336.8 2107.21   363.3 2107.66   379.8 2105.73
   391.5  2102.8   399.1 2101.54   412.9 2102.75   439.3 2107.77   488.9 2109.64
  547.76 2110.32   578.2 2110.53   594.7 2112.89   614.6 2117.24   677.4 2121.52
   710.5 2125.78   720.4 2125.94   746.9 2132.87   799.3 2151.01     850 2166.64
#Mann= 5 ,-1 , 0
       0      .1       0  197.19     .05       0   391.5    .045       0
   412.9     .06       0  547.76      .1       0
Bank Sta=391.5,412.9
XS Rating Curve= 0 ,0
Exp/Cntr(USF)=0,0
Exp/Cntr=0.3,0.1

Type RM Length L Ch R = 1 ,15563   ,237.7,237.7,237.7
XS GIS Cut Line= 2
2199885.08293672322800.9072824942200726.42967419322921.885244744
#Sta/Elev= 30
       0 2195.28    31.7 2192.04    68.6 2182.68   100.5  2171.5   177.5 2135.27
  207.172126.345   237.2 2112.63   257.1 2101.75   313.4 2100.44   367.1 2101.43
   386.4 2099.16   394.12096.445   399.6 2095.49   406.2 2096.28   429.4  2101.9
  457.542102.272   525.6 2104.33  538.312112.047     567 2133.49   581.9 2141.45
   608.4 2144.73   693.9 2148.77     709 2162.05   717.8 2166.29   731.1 2176.83
   737.7  2179.6   747.6 2180.76   767.5 2194.47   798.8 2206.85     850 2222.31
#Mann= 6 ,-1 , 0
       0      .1       0  207.17     .05       0   394.1    .045       0
   406.2     .05       0  457.54     .06       0  538.31     .05       0
#XS Ineff= 2 , 0
          363.51 2101.54
Permanent Ineff=
       F       F
Bank Sta=394.1,406.2
XS Rating Curve= 0 ,0
Exp/Cntr(USF)=0,0
Exp/Cntr=0.3,0.1

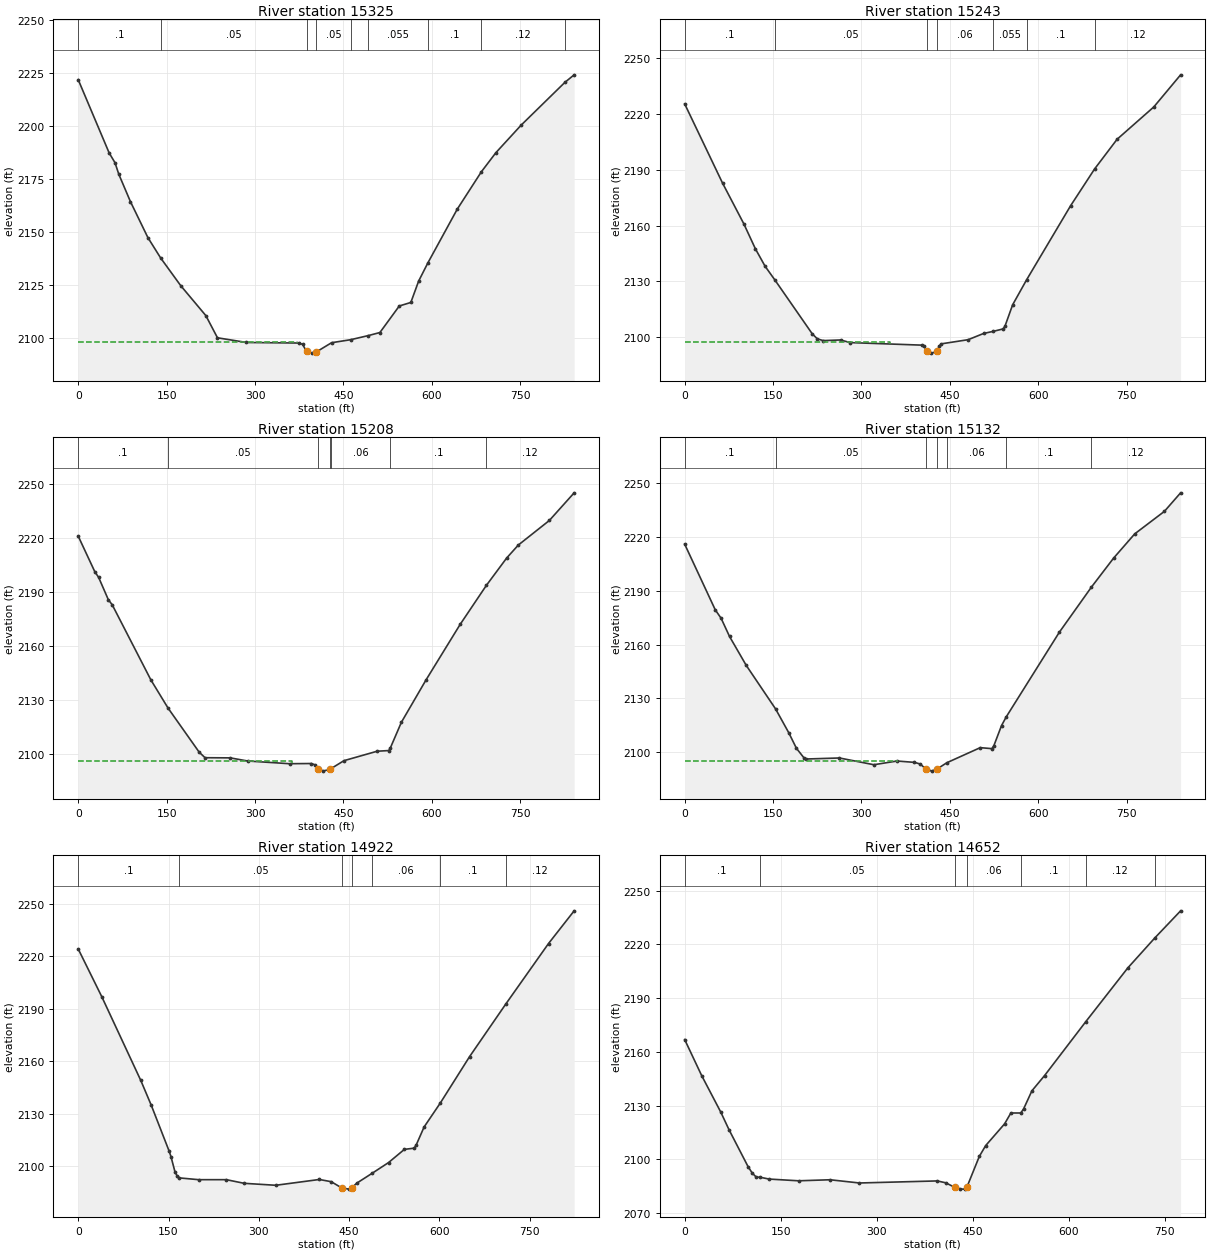
Type RM Length L Ch R = 1 ,15325   ,81.7,81.7,81.7
XS GIS Cut Line= 2
2199860.65664331 323085.404520182200702.00338078323102.681133205
#Sta/Elev= 30
       0 2221.83    52.5 2187.23    62.4 2182.62    68.9 2177.15    88.6 2164.24
   118.2 2147.26  139.762137.671   173.9 2124.56   216.6 2110.39   236.3 2099.92
   285.5 2097.71     374 2097.45   380.7 2096.84   387.4 2093.47   397.1 2092.68
   404.1 2093.25   429.9  2097.6  462.242099.019   492.12100.955   511.9 2102.41
   544.8 2114.95   564.4 2116.61   577.6 2126.69  593.082135.182   643.2  2160.7
  684.242178.396   708.8 2187.38   751.5 2200.34  826.042220.626   841.5 2224.12
#Mann= 9 ,-1 , 0
       0      .1       0  139.76     .05       0   387.4    .045       0
   404.1     .05       0  462.24     .06       0   492.1    .055       0
  593.08      .1       0  684.24     .12       0  826.04      .1       0
#XS Ineff= 2 , 0
          370.63 2097.75
Permanent Ineff=
       F       F
Bank Sta=387.4,404.1
XS Rating Curve= 0 ,0
Exp/Cntr(USF)=0,0
Exp/Cntr=0.5,0.3

Type RM Length L Ch R = 1 ,15243   ,35.5,35.5,35.5
XS GIS Cut Line= 2
 2199842.3848324 323166.177651742200683.73156987323183.454264765
#Sta/Elev= 30
       0 2225.47    64.2 2182.88   100.3 2160.97     120 2147.48   136.4 2138.13
  153.612130.469   216.5 2101.73     225 2099.07   234.9  2098.1   264.4 2098.44
   280.8 2097.03   402.2 2095.66   405.5  2095.4   411.62092.385   418.6 2091.36
   428.5 2092.31   431.8 2094.93   435.1 2096.34     481 2098.59   507.2 2101.94
  523.59 2103.08   540.1 2104.37   543.3 2105.71   556.5 2117.38  580.072130.759
   654.9  2170.7  695.632190.492   733.7 2206.42     796 2223.82   841.5  2241.1
#Mann= 7 ,-1 , 0
       0      .1       0  153.61     .05       0   411.6    .045       0
   428.5     .06       0  523.59    .055       0  580.07      .1       0
  695.63     .12       0
#XS Ineff= 2 , 0
          348.58 2097.24
Permanent Ineff=
       F       F
Bank Sta=411.6,428.5
XS Rating Curve= 0 ,0
Exp/Cntr(USF)=0,0
Exp/Cntr=0.5,0.3

Type RM Length L Ch R = 1 ,15208   ,76,76,76
XS GIS Cut Line= 2
 2199842.3848324323201.5545390612200683.73156987323218.831152086
#Sta/Elev= 30
       0 2221.29    28.1 2201.56    34.7 2198.34    51.1 2185.97    57.7 2183.14
   123.3 2141.39   152.52125.696   205.3 2101.21   215.2 2098.15   257.9 2098.06
   287.4 2096.32   358.7 2094.81   395.7 2094.92   402.2 2094.13   407.72091.714
   415.4 2090.69   427.5 2091.77  428.362091.968   450.9  2096.5   507.2 2101.75
   526.9 2102.12  529.35 2103.36   548.4 2117.87   590.2  2141.4   648.1 2172.25
  692.642193.955   727.1 2209.17   746.8 2216.35   799.4 2229.99   841.5 2245.36
#Mann= 7 ,-1 , 0
       0      .1       0   152.5     .05       0   407.7    .045       0
   427.5     .05       0  428.36     .06       0  529.35      .1       0
  692.64     .12       0
#XS Ineff= 2 , 0
          362.65 2096.12
Permanent Ineff=
       F       F
Bank Sta=407.7,427.5
XS Rating Curve= 0 ,0
Exp/Cntr(USF)=0,0
Exp/Cntr=0.5,0.3

Type RM Length L Ch R = 1 ,15132   ,210.3,210.3,210.3
XS GIS Cut Line= 2
 2199838.3042445323277.4161752852200679.65098197 323294.69278831
#Sta/Elev= 30
       0 2216.07    51.9 2179.43    61.8 2174.74    76.1 2164.58   104.4 2148.48
  154.192124.198   176.6 2110.89   189.7 2102.17   202.9 2096.68   206.1 2096.24
   262.6 2096.81     321 2093.05   360.4 2095.12   389.9 2094.36   399.8 2093.44
   409.6 2090.52   419.4 2089.48   428.7 2090.75  444.812094.159   501.5 2102.57
   521.2 2102.02   524.5 2103.56   537.6 2114.86  545.792119.835   635.6 2166.89
  690.282192.163   727.9 2208.33   763.7 2221.82     814 2234.36   841.5 2244.69
#Mann= 7 ,-1 , 0
       0      .1       0  154.19     .05       0   409.6    .045       0
   428.7     .05       0  444.81     .06       0  545.79      .1       0
  690.28     .12       0
#XS Ineff= 2 , 0
          362.39 2095.09
Permanent Ineff=
       F       F
Bank Sta=409.6,428.7
XS Rating Curve= 0 ,0
Exp/Cntr(USF)=0,0
Exp/Cntr=0.3,0.1

Type RM Length L Ch R = 1 ,14922   ,269.5,269.5,269.5
XS GIS Cut Line= 2
2199818.33684838323472.6181726432200641.03346554323515.777059428
#Sta/Elev= 30
       0 2224.27    39.1 2197.02   103.9 2149.17   121.3    2135     151 2108.77
   154.1 2105.57   160.7 2096.96     164 2094.76  168.032093.432   200.1 2092.42
   246.1 2092.42   275.7 2090.34   328.2 2089.22   400.5 2092.53   420.2 2091.28
   437.9 2087.68   449.8 2087.02   454.2 2087.75   462.8 2090.45  487.922096.007
   515.5  2102.2   541.8 2109.74   558.2 2110.44   561.5 2112.31   574.6 2122.57
  601.432136.205   650.1 2162.75  710.622192.997   781.2 2227.37   823.8 2246.07
#Mann= 7 ,-1 , 0
       0      .1       0  168.03     .05       0   437.9    .045       0
   454.2     .05       0  487.92     .06       0  601.43      .1       0
  710.62     .12       0
#XS Ineff= 2 , 0
             401 2092.47
Permanent Ineff=
       F       F
Bank Sta=437.9,454.2
XS Rating Curve= 0 ,0
Exp/Cntr(USF)=0,0
Exp/Cntr=0.3,0.1

Type RM Length L Ch R = 1 ,14652   ,223.3,223.3,223.3
XS GIS Cut Line= 2
2199837.31130273323739.6158517212200611.04823933323785.775990136
#Sta/Elev= 30
       0 2166.87    26.7 2146.64    56.2 2126.51    69.4 2116.45      99 2095.96
   105.6  2092.3   112.2 2089.96  117.262090.032   131.9 2088.97   177.9    2088
   227.2 2088.58   273.1 2086.78   394.8 2087.93     408 2086.88   422.2 2084.31
     431 2083.35   437.5 2083.38   440.9  2084.3   460.5 2101.63   470.4 2107.65
     500  2119.8   509.8 2125.86  525.222125.862   529.6 2128.07   542.7 2138.25
   562.4 2146.72  627.012176.912   692.5 2206.84   734.82223.609   775.1 2238.74
#Mann= 7 ,-1 , 0
       0      .1       0  117.26     .05       0   422.2    .045       0
   440.9     .06       0  525.22      .1       0  627.01     .12       0
   734.8      .1       0
#XS Ineff= 2 , 0
          393.41 2087.88
Permanent Ineff=
       F       F
Bank Sta=422.2,440.9
XS Rating Curve= 0 ,0
Exp/Cntr(USF)=0,0
Exp/Cntr=0.3,0.1

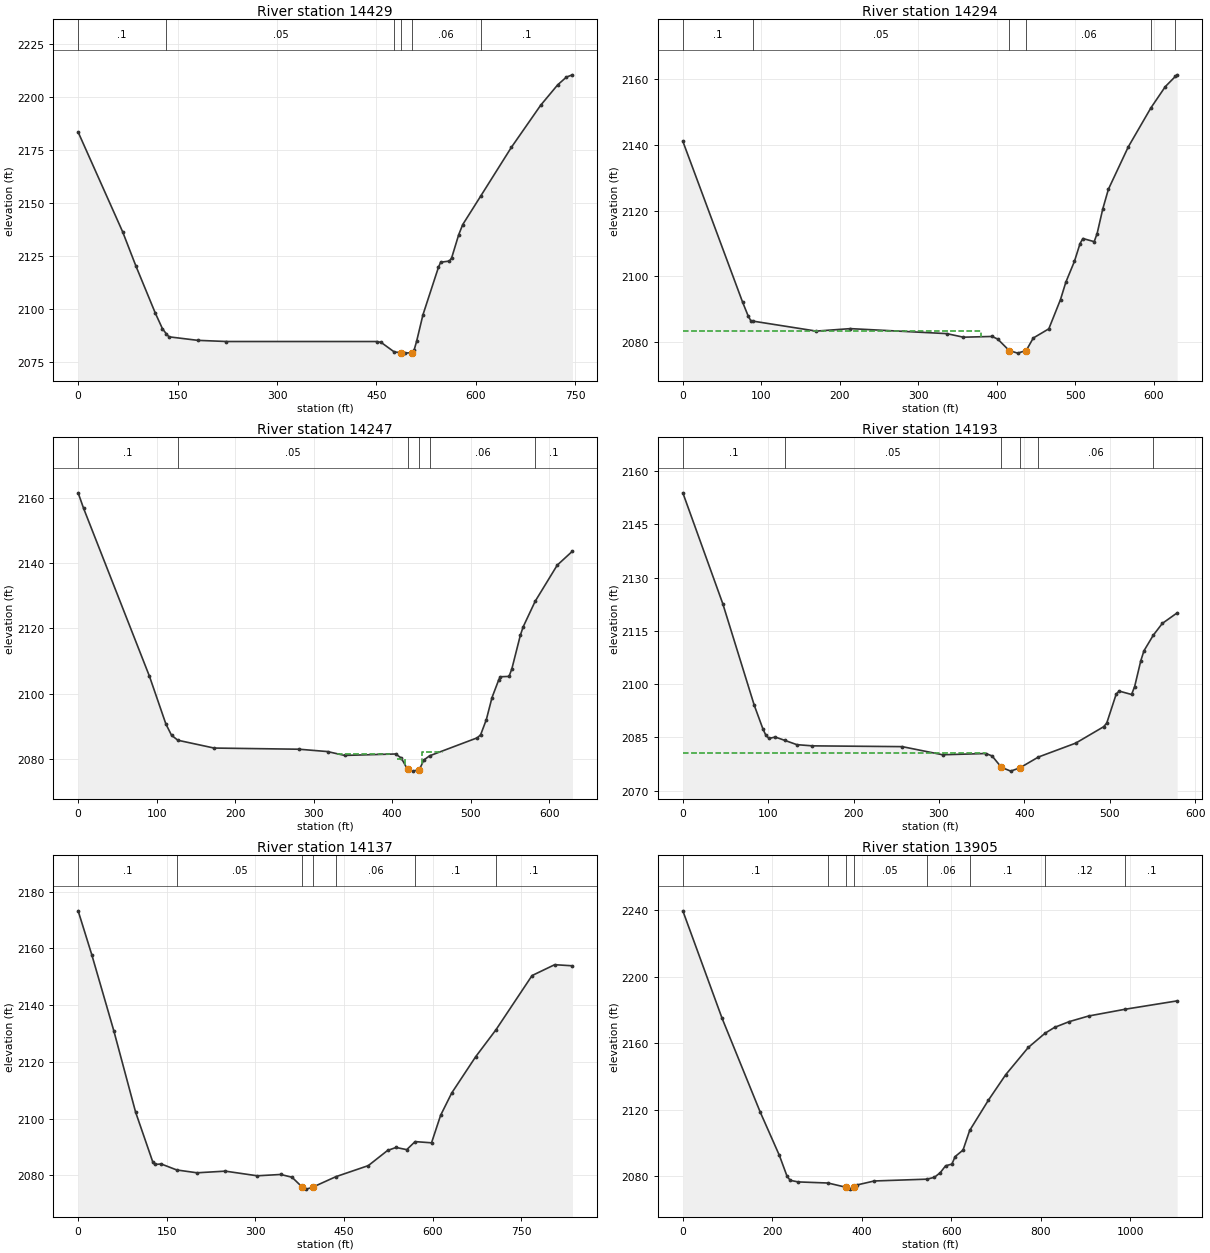
Type RM Length L Ch R = 1 ,14429   ,135.3,135.3,135.3
XS GIS Cut Line= 2
2199801.04790471323897.424030629  2200535.520096324025.558166831
#Sta/Elev= 30
       0 2183.63    67.2 2136.48    87.2 2120.32   116.4 2098.13   127.1 2090.81
  132.932088.345   137.1 2086.92   180.4 2085.26   223.7 2084.71   450.2  2084.7
   456.9 2084.31  476.992079.736   487.42079.492   493.5 2079.22   503.5 2079.48
   506.8 2080.71   510.6 2084.89   520.1 2097.34   543.4  2119.7   546.8 2122.15
   560.1 2122.71   563.4 2124.24     574 2135.14   580.1 2139.95  607.032153.315
   653.3 2176.35   697.7 2196.33   723.3 2205.94   736.6 2209.63   745.6 2210.67
#Mann= 6 ,-1 , 0
       0      .1       0  132.93     .05       0  476.99     .06       0
   487.4    .045       0   503.5     .06       0  607.03      .1       0
Bank Sta=487.4,503.5
XS Rating Curve= 0 ,0
Exp/Cntr(USF)=0,0
Exp/Cntr=0.3,0.1

Type RM Length L Ch R = 1 ,14294   ,46.8,46.8,46.8
XS GIS Cut Line= 2
2199860.44067001 323931.646713062200432.38493687324195.141965787
#Sta/Elev= 30
       0 2141.18    76.1 2092.21    83.3 2087.94      87 2086.37   89.78 2086.39
     170 2083.37   213.4 2084.12   336.2  2082.6   357.4 2081.51     394 2081.74
   401.2 2080.92   415.7 2077.45   426.5 2076.66   437.4 2077.45   446.4 2081.26
   466.2 2084.06   481.1 2092.99   487.9 2098.27   498.8 2104.59     506 2110.04
   509.6 2111.57     524 2110.61   527.7 2113.04   534.9 2120.54   542.1 2126.57
   567.4 2139.46  596.272151.369   614.6 2157.83  627.39 2160.93   629.7 2161.42
#Mann= 6 ,-1 , 0
       0      .1       0   89.78     .05       0   415.7    .045       0
   437.4     .06       0  596.27      .1       0  627.39      .1       0
#XS Ineff= 2 , 0
           380.3 2083.36
Permanent Ineff=
       F       F
Bank Sta=415.7,437.4
XS Rating Curve= 0 ,0
Exp/Cntr(USF)=0,0
Exp/Cntr=0.5,0.3

Type RM Length L Ch R = 1 ,14247   ,53.9,53.9,53.9
XS GIS Cut Line= 2
 2199834.6006664323970.0199402662200406.54493326324233.515192993
#Sta/Elev= 30
       0 2161.58       7 2156.79    90.8 2105.33   111.8 2090.64     119 2087.19
  127.042085.665   173.2 2083.27   281.6 2082.91   317.7 2082.19   339.4 2081.01
   404.4 2081.45   411.6 2080.22   419.7 2076.69   426.1 2076.19   434.5  2076.6
   440.5 2079.62  447.692080.889   508.7 2086.44   512.8 2087.39     520 2092.01
   527.2 2098.76   535.9 2104.28     538 2105.15   548.9 2105.25   552.5 2107.58
   563.3 2117.87   566.9 2120.46   582.22128.305   610.3 2139.39   629.7 2143.68
#Mann= 6 ,-1 , 0
       0      .1       0  127.04     .05       0   419.7    .045       0
   434.5     .05       0  447.69     .06       0   582.2      .1       0
#XS Ineff= 3 ,-1
  330.06   397.6 2081.51  406.68  416.33 2080.02  438.18  465.14 2082.01
Permanent Ineff=
       F       F       F
Bank Sta=419.7,434.5
XS Rating Curve= 0 ,0
Exp/Cntr(USF)=0,0
Exp/Cntr=0.5,0.3

Type RM Length L Ch R = 1 ,14193   ,56.3,56.3,56.3
XS GIS Cut Line= 2
2199848.15384808324031.0092578222200371.57369719324278.467651835
#Sta/Elev= 30
       0  2153.9    46.8 2122.66    83.7 2094.02    93.7 2087.46    97.3 2085.57
     101 2084.72   108.2  2085.1  119.522084.159   133.6 2082.95   151.8 2082.62
     257  2082.4   304.2 2080.11     355 2080.46   362.2 2079.78   373.1 2076.58
     384  2075.5   394.9 2076.44  416.512079.475   460.2 2083.39   492.9 2088.01
   496.5 2089.02   507.6 2097.21     511 2098.05   525.6 2097.09   529.2 2099.32
   536.4 2106.59   540.1  2109.4     551 2113.78   561.6 2117.11     579 2120.08
#Mann= 6 ,-1 , 0
       0      .1       0  119.52     .05       0   373.1    .045       0
   394.9     .05       0  416.51     .06       0     551      .1       0
#XS Ineff= 2 , 0
          354.42  2080.5
Permanent Ineff=
       F       F
Bank Sta=373.1,394.9
XS Rating Curve= 0 ,0
Exp/Cntr(USF)=0,0
Exp/Cntr=0.5,0.3

Type RM Length L Ch R = 1 ,14137   ,231.6,231.6,231.6
XS GIS Cut Line= 3
2199811.64921597324079.3763933632200349.33572889324327.089067168
2200548.85334089324185.515528964
#Sta/Elev= 30
       0 2173.22    23.2 2157.67    60.3 2130.99    97.3 2102.23   126.2 2084.77
   129.8 2083.81   140.7 2083.97  166.952081.865   201.2 2080.87   249.1 2081.45
   303.2 2079.81     343 2080.28     362 2079.29   379.5 2075.78   386.3 2075.11
   396.92075.789   436.2  2079.5   491.1  2083.4   523.6 2088.73     538  2089.8
   556.1 2089.03  570.312091.859   598.1 2091.44   613.5 2101.16   632.3 2109.02
   672.7 2121.76  707.192131.306   768.2  2150.4   806.5 2154.23   836.6 2153.84
#Mann= 7 ,-1 , 0
       0      .1       0  166.95     .05       0   379.5    .045       0
   396.9     .05       0   436.2     .06       0  570.31      .1       0
  707.19      .1       0
Bank Sta=379.5,396.9
XS Rating Curve= 0 ,0
Exp/Cntr(USF)=0,0
Exp/Cntr=0.3,0.1

Type RM Length L Ch R = 1 ,13905   ,129,129,129
XS GIS Cut Line= 3
 2199690.9369406324293.9409823962200393.61159006 324580.96571209
2200702.00429386324424.051526516
#Sta/Elev= 30
       0  2239.5    87.7  2174.9   172.7 2118.65   215.8 2092.42     233 2079.87
   240.1  2077.4   257.8 2076.46  324.672075.793   363.8  2073.3   374.7 2072.12
   381.8 2073.21   388.9  2074.6   427.9 2077.02  545.722078.112   562.6 2079.25
   575.6 2082.06   587.4 2086.15   601.6 2087.19   608.6 2091.66   626.4 2095.61
  641.212107.387   683.1 2125.61     722 2141.02   772.2 2157.31  809.832165.891
     831  2169.4   863.7 2172.85   907.1 2176.24  989.322180.331  1105.1 2185.34
#Mann= 8 ,-1 , 0
       0      .1       0  324.67     .05       0   363.8    .045       0
   381.8     .05       0  545.72     .06       0  641.21      .1       0
  809.83     .12       0  989.32      .1       0
Bank Sta=363.8,381.8
XS Rating Curve= 0 ,0
Exp/Cntr(USF)=0,0
Exp/Cntr=0.3,0.1