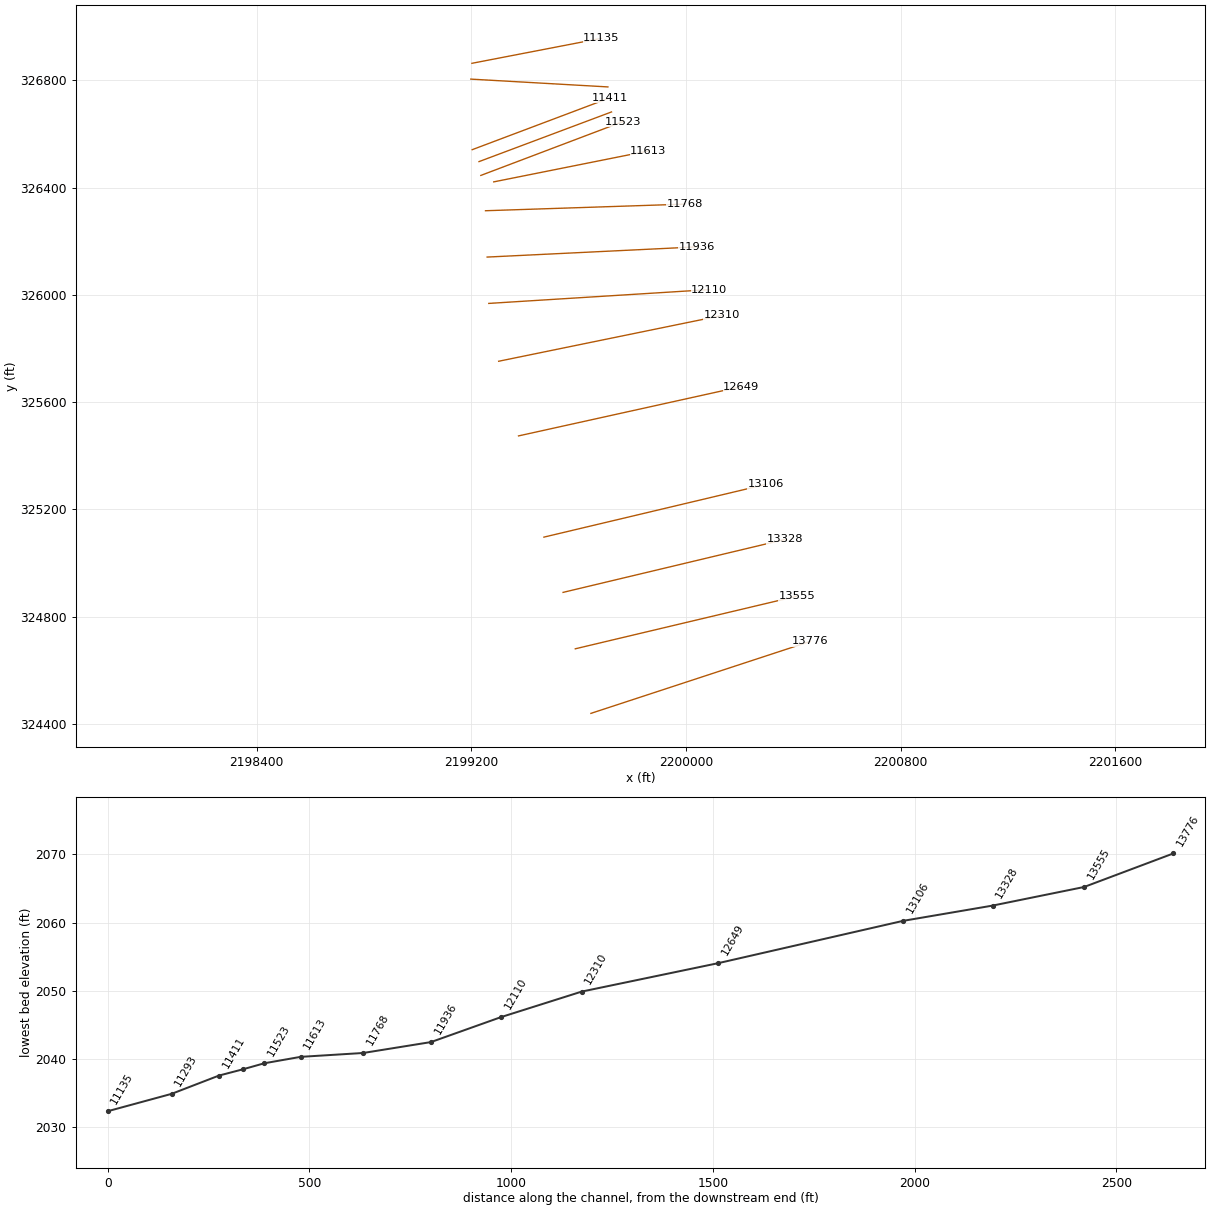
HEC-RAS study ANTNYCKT2.prj: ANTNYCKT2

--- ANTNYCKT2.g02 (geometry) --- (continued)

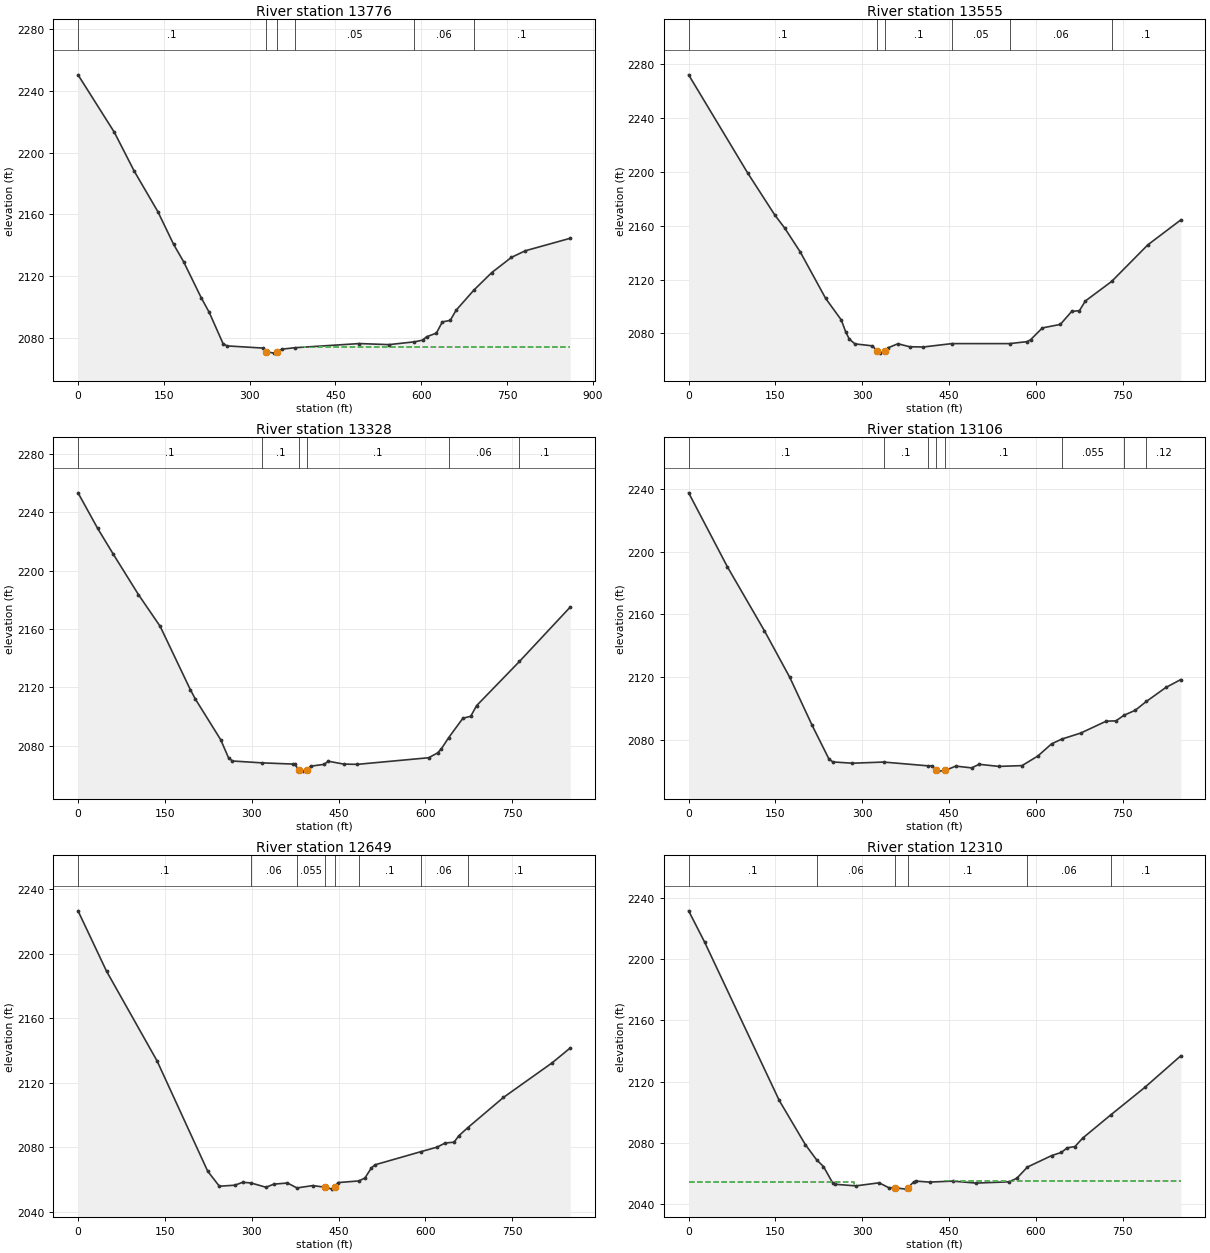
Type RM Length L Ch R = 1 ,13776   ,221.5,221.5,221.5
XS GIS Cut Line= 2
2199646.01986191324438.9600263632200463.46829631324707.313023609
#Sta/Elev= 30
       0 2250.38    63.6  2213.1    98.2 2188.06   139.6 2161.76   167.2 2140.55
   184.5 2129.42   215.6 2105.86   229.4 2096.53   253.6 2076.28   260.6 2074.84
   322.6 2073.45   328.2    2071   343.3 2070.16   348.52071.115   356.8 2072.75
  379.222073.661   491.8 2076.35   543.6 2075.67  587.692077.455   602.3 2078.54
   609.2 2080.73   626.5 2083.12   636.9 2090.38   650.7 2091.37     661 2097.96
  692.272111.066   723.2 2122.29   757.7 2132.18   781.9 2136.44   860.4 2144.53
#Mann= 6 ,-1 , 0
       0      .1       0   328.2    .045       0   348.5      .1       0
  379.22     .05       0  587.69     .06       0  692.27      .1       0
#XS Ineff= 2 , 0
                           390.6         2074.13
Permanent Ineff=
       F       F
Bank Sta=328.2,348.5
XS Rating Curve= 0 ,0
Exp/Cntr(USF)=0,0
Exp/Cntr=0.3,0.1

Type RM Length L Ch R = 1 ,13555   ,226.8,226.8,226.8
XS GIS Cut Line= 2
2199587.84471598324679.7834230622200414.82529215324876.260207038
#Sta/Elev= 30
       0  2272.3   101.7 2199.45   148.9 2167.94   165.8 2158.35   192.8 2140.49
   236.6 2105.97   263.6 2089.93   271.3 2081.02   277.5 2075.66   287.2 2072.11
   317.5 2070.63   325.8 2066.67     331 2065.23   339.4 2066.76   344.5  2069.2
   361.4 2072.21   381.6 2069.98   405.2 2069.79  454.812072.321  554.512072.316
   584.7 2073.79   590.7 2075.27   610.9 2083.98   641.9 2086.59   661.5 2096.23
     675 2096.87   685.1 2104.01  730.532118.563     793 2145.78     850 2164.36
#Mann= 6 ,-1 , 0
       0      .1       0   325.8    .045       0   339.4      .1       0
  454.81     .05       0  554.51     .06       0  730.53      .1       0
#XS Ineff= 2 , 0
                          364.13         2070.72
Permanent Ineff=
       F       F
Bank Sta=325.8,339.4
XS Rating Curve= 0 ,0
Exp/Cntr(USF)=0,0
Exp/Cntr=0.3,0.1

Type RM Length L Ch R = 1 ,13328   ,221.8,221.8,221.8
XS GIS Cut Line= 2
2199542.23633219324890.1551302452200368.99074673325087.581415304
#Sta/Elev= 30
       0 2253.37    33.9 2228.98    60.9  2211.3   104.4 2183.55   141.9 2161.77
   193.9 2118.45   202.6 2111.95   246.4 2084.04   259.9 2071.67   266.7 2069.45
  317.182068.185   371.3 2067.34   374.6 2067.08   381.4 2063.17   388.1  2062.5
   394.9 2063.07   401.6 2065.88   425.2 2067.16     432 2069.31     459 2067.32
   482.6 2067.16   605.5 2071.68   620.9 2074.96   627.6 2077.86  640.062085.418
   664.7 2098.78   678.2 2100.12   688.3 2107.39   762.32137.697     850 2174.99
#Mann= 6 ,-1 , 0
       0      .1       0  317.18      .1       0   381.4    .045       0
   394.9      .1       0  640.06     .06       0   762.3      .1       0
#XS Ineff= 2 , 0
                           443.1         2067.19
Permanent Ineff=
       F       F
Bank Sta=381.4,394.9
XS Rating Curve= 0 ,0
Exp/Cntr(USF)=0,0
Exp/Cntr=0.3,0.1

Type RM Length L Ch R = 1 ,13106   ,457.5,457.5,457.5
XS GIS Cut Line= 2
2199470.77942695325096.2043508472200297.74314229325292.752089315
#Sta/Elev= 30
       0 2237.44    66.9 2190.36     131 2149.55   174.8 2119.87   213.4 2089.32
   242.3    2068     249 2066.12   282.7  2065.3  336.932066.034     4132063.643
     421 2063.63   427.7 2060.74   431.1 2060.26   442.92060.663   461.4 2063.46
   488.6 2062.33   501.9  2064.6   535.7 2063.27   575.8 2063.77   603.2  2069.9
   626.7  2077.6  644.332080.649   677.3 2084.51   721.1 2092.06     738 2092.28
  751.912095.832   771.3    2099  790.572104.643   824.3 2113.55     850 2118.56
#Mann= 8 ,-1 , 0
       0      .1       0  336.93      .1       0     413      .1       0
   427.7    .045       0   442.9      .1       0  644.33    .055       0
  751.91      .1       0  790.57     .12       0
#XS Ineff= 2 , 0
                          502.87         2064.27
Permanent Ineff=
       F       F
Bank Sta=427.7,442.9
XS Rating Curve= 0 ,0
Exp/Cntr(USF)=0,0
Exp/Cntr=0.3,0.1

Type RM Length L Ch R = 1 ,12649   ,338.9,338.9,338.9
XS GIS Cut Line= 2
2199376.29222137 325473.67424764 2200206.2065343325657.364838581
#Sta/Elev= 30
       0 2226.67    49.2 2189.26   136.6 2133.52   223.9 2065.22   244.1 2055.86
     271  2056.5   284.4 2058.31  298.742057.887   324.7 2055.22   338.2 2057.17
   361.7 2057.85  378.112054.802   405.4 2056.26   426.7 2055.24     439 2054.06
   443.32055.259   449.1 2058.12  485.012059.146   495.5 2060.95   506.5 2067.14
   512.9 2069.15  591.912077.268   620.4 2080.14   633.9 2082.64   649.5 2083.19
   657.4 2087.07  672.722092.057   734.7 2110.93   818.7 2132.36     850 2141.59
#Mann= 8 ,-1 , 0
       0      .1       0  298.74     .06       0  378.11    .055       0
   426.7    .045       0   443.3    .055       0  485.01      .1       0
  591.91     .06       0  672.72      .1       0
#XS Ineff= 2 , 0
          285.45 2058.27
Permanent Ineff=
       F       F
Bank Sta=426.7,443.3
XS Rating Curve= 0 ,0
Exp/Cntr(USF)=0,0
Exp/Cntr=0.3,0.1

Type RM Length L Ch R = 1 ,12310   ,199.7,199.7,199.7
XS GIS Cut Line= 2
2199302.26472039325752.0674351022200134.93177768325922.846742118
#Sta/Elev= 30
       0 2231.38    27.5 2211.05   156.5  2107.7   201.6 2078.89  220.882069.055
   232.9 2064.61   248.5 2054.11   252.3 2053.07   288.7    2052   328.9    2054
   345.7 2050.81   355.7 2050.76   375.8 2049.88   379.1 2050.85   388.5 2054.57
   392.5 2055.12     416 2054.47   456.2  2055.1   496.4 2053.82   553.3 2054.64
   566.7 2056.94  585.172064.292     627 2071.76   643.7 2073.82   653.8 2076.81
   667.2 2077.65   680.6 2083.18  729.472098.431   787.7 2116.18     850 2136.85
#Mann= 6 ,-1 , 0
       0      .1       0  220.88     .06       0   355.7    .045       0
   379.1      .1       0  585.17     .06       0  729.47      .1       0
#XS Ineff= 2 , 0
          286.32  2054.7  441.27         2055.17
Permanent Ineff=
       F       F
Bank Sta=355.7,379.1
XS Rating Curve= 0 ,0
Exp/Cntr(USF)=0,0
Exp/Cntr=0.3,0.1

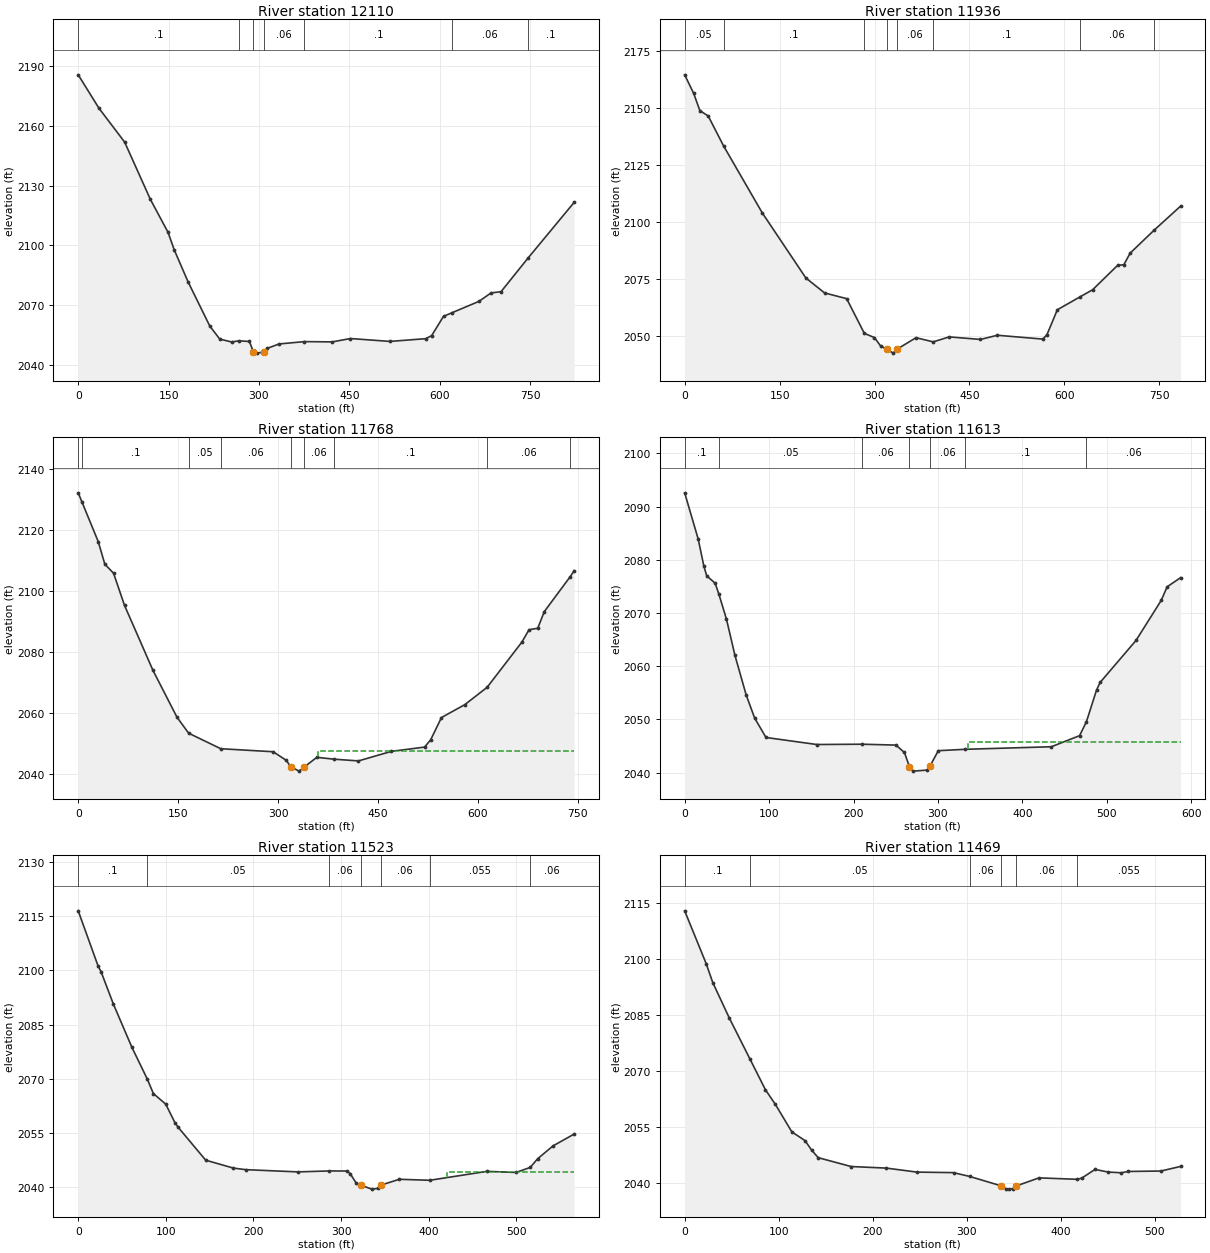
Type RM Length L Ch R = 1 ,12110   ,173.9,173.9,173.9
XS GIS Cut Line= 2
2199265.36703588325967.7589197662200086.84102801326019.261010146
#Sta/Elev= 30
       0 2185.38    34.4 2168.68    77.1 2151.71   119.8 2123.04   149.1 2106.58
   159.3 2097.86   182.3 2081.82   218.4 2059.68   234.9 2053.17   254.6 2051.72
  266.532052.305   284.2 2051.96   290.8 2046.72   297.3 2046.14     3082046.712
   313.8 2048.54   333.5 2050.73  375.482051.905   421.6 2051.76   451.8 2053.44
   517.5    2052   576.8 2053.37   586.6  2054.9   606.3 2064.55  621.022066.432
     665 2072.02   685.2 2076.27   701.7 2076.87  746.22 2093.58   823.1 2121.58
#Mann= 7 ,-1 , 0
       0      .1       0  266.53     .06       0   290.8    .045       0
     308     .06       0  375.48      .1       0  621.02     .06       0
  746.22      .1       0
Bank Sta=290.8,308
XS Rating Curve= 0 ,0
Exp/Cntr(USF)=0,0
Exp/Cntr=0.3,0.1

Type RM Length L Ch R = 1 ,11936   ,168,168,168
XS GIS Cut Line= 2
2199259.26810412326140.5619861742200042.09946259326178.658954369
#Sta/Elev= 30
       0 2164.57    14.2 2156.44      24 2148.87    37.2 2146.51   61.482133.375
   122.6 2104.01   191.5 2075.45   221.1 2068.88     256 2066.37  283.952051.136
   299.9 2049.29   309.8 2045.55   319.6 2044.19   329.5 2042.47   336.1 2044.28
   365.6 2049.24  392.72 2047.41   418.1 2049.59   467.5 2048.48   494.2 2050.31
     566 2048.63   572.6 2050.59     589 2061.51  624.512067.107   644.8 2070.29
   684.1 2080.95   694.1 2081.27     704 2086.33   742.3 2096.51   783.8 2106.97
#Mann= 8 ,-1 , 0
       0     .05       0   61.48      .1       0  283.95     .06       0
   319.6    .045       0   336.1     .06       0  392.72      .1       0
  624.51     .06       0   742.3      .1       0
Bank Sta=319.6,336.1
XS Rating Curve= 0 ,0
Exp/Cntr=0.3,0.1

Type RM Length L Ch R = 1 ,11768   ,155.1,155.1,155.1
XS GIS Cut Line= 2
2199253.16917236326313.3650525832199997.35789718326338.056898591
#Sta/Elev= 30
       0 2132.19    5.482129.264    30.1 2116.16      40 2108.76    53.1  2105.8
    69.5 2095.26   112.2 2073.95   148.3 2058.56  165.812053.315  214.032048.225
   292.7 2047.23   312.4 2044.41     319 2042.32   331.6 2040.87   339.32042.228
   358.4 2045.41  383.41  2044.8   420.7 2044.22     470 2047.34     520 2048.76
   529.1 2051.12   545.4 2058.46   580.4 2062.68  613.912068.366   666.2 2083.23
   676.8 2087.26   689.9 2087.75   699.8 2093.22  738.552104.637   744.6 2106.63
#Mann= 9 ,-1 , 0
       0     .05       0    5.48      .1       0  165.81     .05       0
  214.03     .06       0     319    .045       0   339.3     .06       0
  383.41      .1       0  613.91     .06       0  738.55      .1       0
#XS Ineff= 2 , 0
                          360.68         2047.57
Permanent Ineff=
       F       F
Bank Sta=319,339.3
XS Rating Curve= 0 ,0
Exp/Cntr(USF)=0,0
Exp/Cntr=0.3,0.1

Type RM Length L Ch R = 1 ,11613   ,89.9,89.9,89.9
XS GIS Cut Line= 2
 2199283.9568779326421.0015386262199859.95103287326536.283856701
#Sta/Elev= 30
       0 2092.58      16  2083.9    22.7 2078.82    26.1 2076.99    36.1 2075.59
   40.612073.495    49.5 2068.85    59.5 2062.06    72.9 2054.58    82.9 2050.26
    96.3 2046.62   156.5  2045.3  210.222045.356   250.2 2045.19   260.3  2043.8
   266.2 2041.13   270.3  2040.3     287 2040.49   290.4  2041.2   300.4 2044.14
  332.582044.402   434.3 2044.88   467.7 2046.96  475.782049.551   487.8 2055.52
     492 2056.95   534.6 2064.86   564.5 2072.39   571.4 2074.92   587.4 2076.65
#Mann= 7 ,-1 , 0
       0      .1       0   40.61     .05       0  210.22     .06       0
   266.2    .045       0   290.4     .06       0  332.58      .1       0
  475.78     .06       0
#XS Ineff= 2 , 0
                          335.06         2045.75
Permanent Ineff=
       F       F
Bank Sta=266.2,290.4
XS Rating Curve= 0 ,0
Exp/Cntr(USF)=0,0
Exp/Cntr=0.3,0.1

Type RM Length L Ch R = 1 ,11523   ,54,54,54
XS GIS Cut Line= 2
2199235.82042388326445.0401169532199765.07216845326645.627205804
#Sta/Elev= 30
       0 2116.53    22.7 2101.22    26.2 2099.58    40.2 2090.63    61.3 2078.67
   78.812069.893    85.8 2065.85    99.8 2062.95   110.4  2057.8     114 2056.53
   145.5 2047.39     177  2045.2   191.1 2044.76   250.7 2044.14  286.542044.404
   306.9 2044.38   310.4 2043.65   317.4 2040.99   322.7 2040.46   334.9 2039.36
   341.9 2039.54   345.2 2040.45   366.5 2042.09  401.212041.813   466.3 2044.28
   499.8 2043.99  515.872045.383   524.4  2047.8   541.9 2051.35     566 2054.63
#Mann= 7 ,-1 , 0
       0      .1       0   78.81     .05       0  286.54     .06       0
   322.7    .045       0   345.2     .06       0  401.21    .055       0
  515.87     .06       0
#XS Ineff= 2 , 0
                          420.44         2044.16
Permanent Ineff=
       F       F
Bank Sta=322.7,345.2
XS Rating Curve= 0 ,0
Exp/Cntr(USF)=0,0
Exp/Cntr=0.5,0.3

Type RM Length L Ch R = 1 ,11469   ,58.6,58.6,58.6
XS GIS Cut Line= 2
2199229.04383304326496.5422073342199722.79446288326681.827091558
#Sta/Elev= 30
       0 2112.85    22.9 2098.71    29.9 2093.66    47.4 2084.23   69.352073.275
    85.9 2065.02    96.5 2061.09     114 2053.75     128 2051.43     135 2048.89
     142 2046.87     177  2044.5   214.5 2044.08   247.1 2043.01   285.9 2042.87
  303.222041.839   336.42039.351   341.9  2038.5   345.3 2038.46   348.8 2038.59
   352.3 2039.28   376.8 2041.47  417.66 2041.08   422.3 2041.41   436.4 2043.73
   450.4 2043.02   464.4 2042.83   471.4 2043.18   506.4  2043.3   527.4 2044.53
#Mann= 6 ,-1 , 0
       0      .1       0   69.35     .05       0  303.22     .06       0
   336.4    .045       0   352.3     .06       0  417.66    .055       0
Bank Sta=336.4,352.3
XS Rating Curve= 0 ,0
Exp/Cntr(USF)=0,0
Exp/Cntr=0.5,0.3

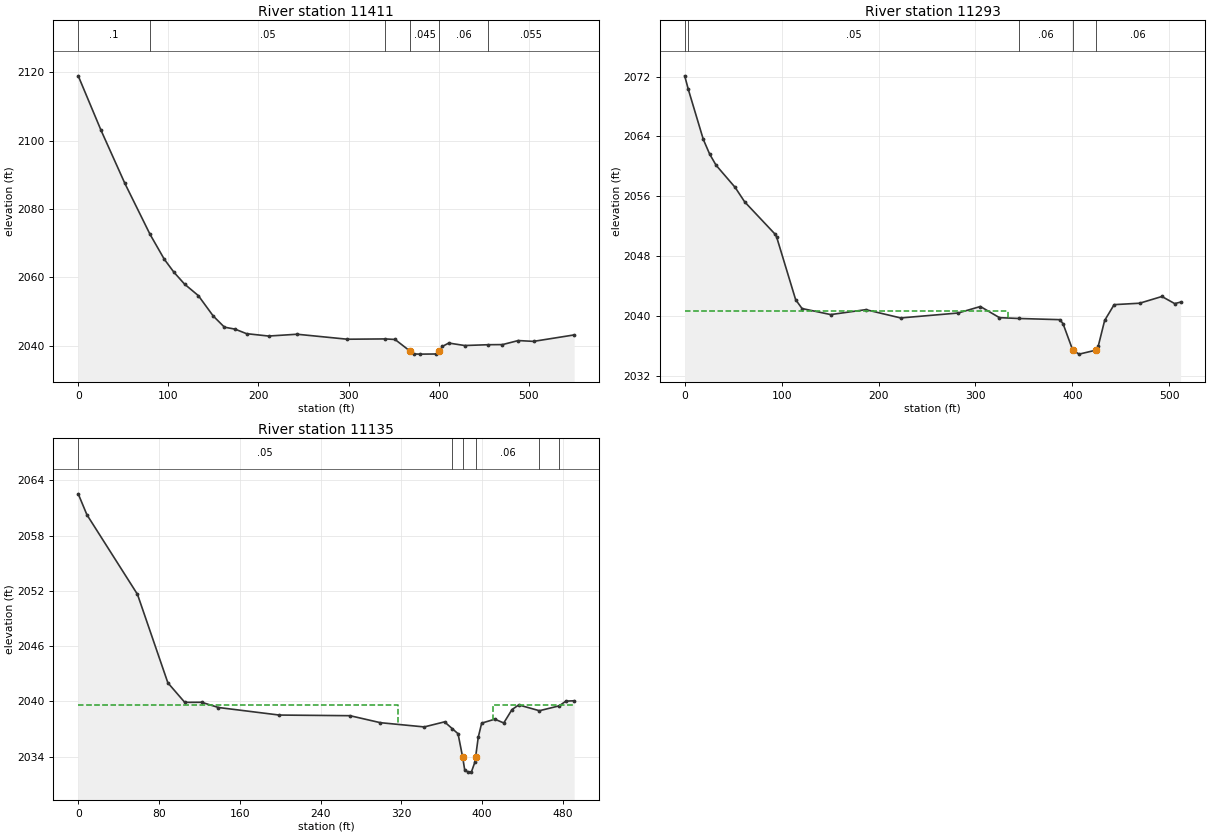
Type RM Length L Ch R = 1 ,11411   ,117.3,117.3,117.3
XS GIS Cut Line= 2
2199203.70005924326541.0585047922199718.56773146326735.096250062
#Sta/Elev= 30
       0 2118.97    25.4 2102.98    51.8 2087.48   79.752072.563    95.5 2065.31
   106.1 2061.54     118 2058.03   133.3 2054.66   149.8  2048.7   162.2 2045.44
     174 2044.86   186.7 2043.54   211.2 2042.84   242.8 2043.37   298.6 2041.91
  340.53    2042   351.5 2041.84   367.6 2038.54   372.5  2037.6   379.5 2037.55
   397.1 2037.59   400.7 2038.52   404.1 2039.82   411.1 2040.79   428.7 2040.07
  455.072040.304   470.7 2040.34   488.2 2041.52   505.1 2041.28   550.2 2043.17
#Mann= 6 ,-1 , 0
       0      .1       0   79.75     .05       0  340.53     .06       0
   367.6    .045       0   400.7     .06       0  455.07    .055       0
Bank Sta=367.6,400.7
XS Rating Curve= 0 ,0
Exp/Cntr(USF)=0,0
Exp/Cntr=0.5,0.3

Type RM Length L Ch R = 1 ,11293   ,158.4,158.4,158.4
XS GIS Cut Line= 2
2199198.46408296326804.2052051212199709.33412245326775.100178306
#Sta/Elev= 30
       0  2072.1    3.772070.277    19.2  2063.6    25.8 2061.62    32.4 2060.14
    52.1 2057.17    61.9 2055.24    93.2 2050.93    94.8 2050.57   114.5 2042.15
   121.1 2040.97   150.7 2040.16   186.8 2040.82   222.9 2039.71   282.1 2040.37
   305.1 2041.24   324.8 2039.75  344.48 2039.64   387.3 2039.48   390.5  2038.9
   400.4  2035.4     407 2034.87   424.2  2035.4   426.7 2035.93   433.3 2039.37
   443.1 2041.49   469.4 2041.68   492.4 2042.58   505.6 2041.63   511.7 2041.83
#Mann= 5 ,-1 , 0
       0      .1       0    3.77     .05       0  344.48     .06       0
   400.4    .045       0   424.2     .06       0
#XS Ineff= 2 , 0
          333.92 2040.61
Permanent Ineff=
       F       F
Bank Sta=400.4,424.2
XS Rating Curve= 0 ,0
Exp/Cntr(USF)=0,0
Exp/Cntr=0.3,0.1

Type RM Length L Ch R = 1 ,11135   ,114,114,114
XS GIS Cut Line= 2
2199202.63144759326863.1454334542199684.89166905326956.272922623
#Sta/Elev= 30
       0 2062.55     8.6 2060.28    58.7 2051.63    88.8 2042.02   105.5  2039.9
   122.2 2039.91   138.9 2039.34   199.1 2038.52   269.2 2038.45   299.3 2037.69
   342.7 2037.23   362.8 2037.78  370.61 2037.03   376.2 2036.49   380.82033.925
   382.8 2032.56   386.2 2032.32   389.5 2032.36   392.9 2033.41   393.62033.962
   396.2  2036.1   399.6 2037.64   412.6 2038.07   421.5 2037.66   429.6 2039.11
   436.3 2039.62   456.8 2038.99  476.422039.521     483 2040.03   491.2 2040.07
#Mann= 6 ,-1 , 0
       0     .05       0  370.61     .06       0   380.8    .045       0
   393.6     .06       0   456.8      .1       0  476.42     .05       0
#XS Ineff= 2 , 0
          316.93 2039.61  410.62         2039.58
Permanent Ineff=
       F       F
Bank Sta=380.8,393.6
XS Rating Curve= 0 ,0
Exp/Cntr(USF)=0,0
Exp/Cntr=0.3,0.1