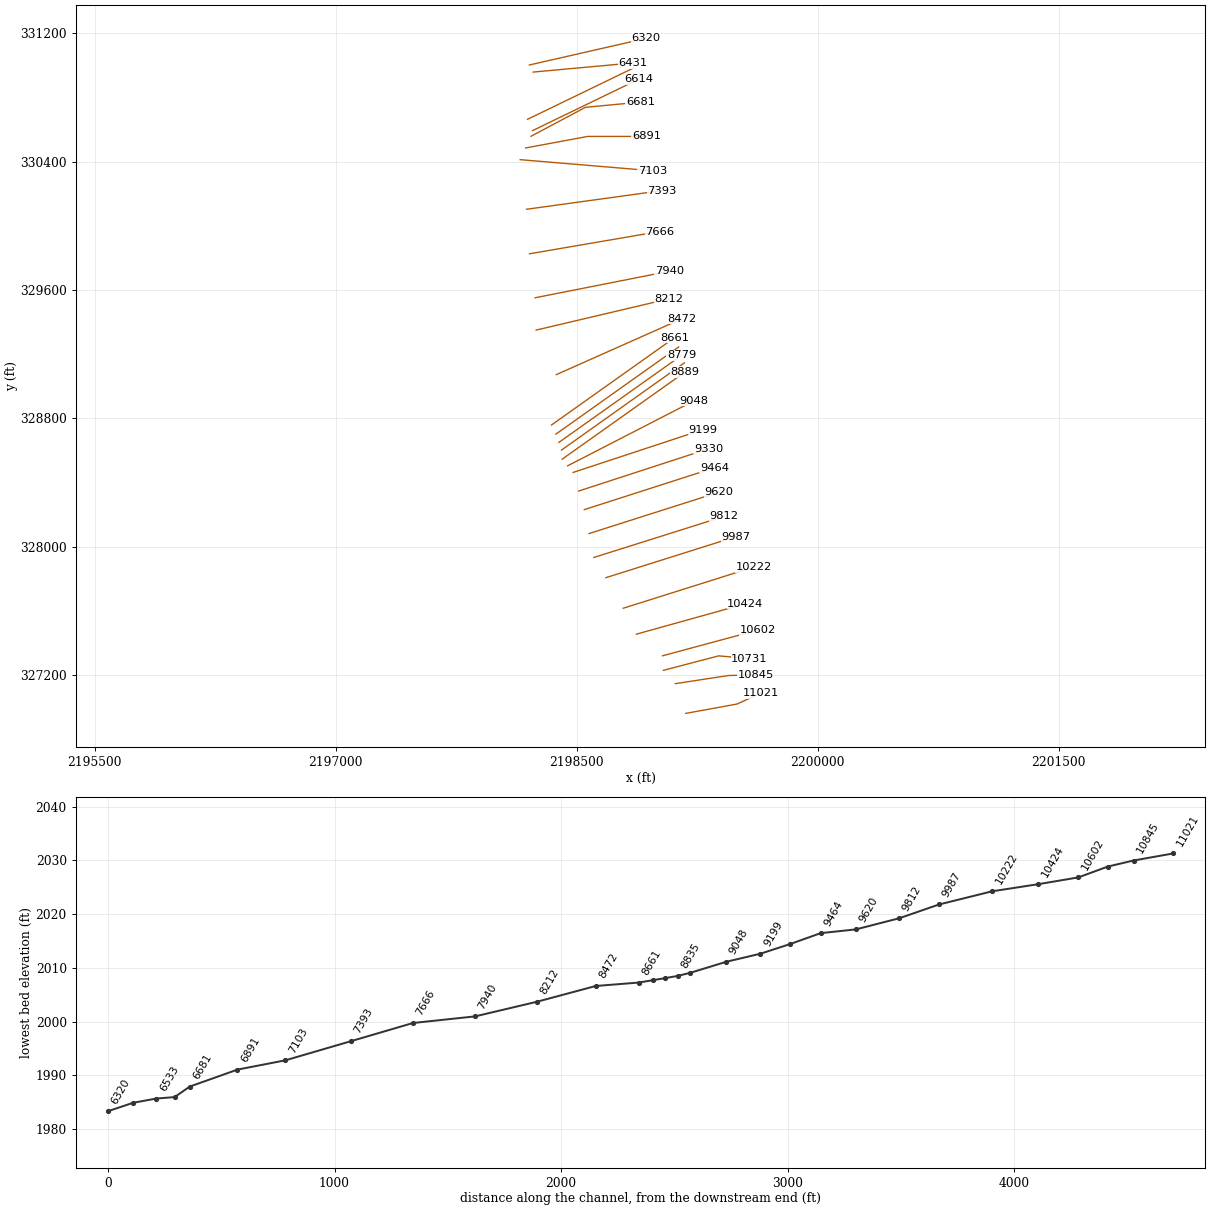
HEC-RAS study ANTNYCKT2.prj: ANTNYCKT2

--- ANTNYCKT2.g02 (geometry) --- (continued)

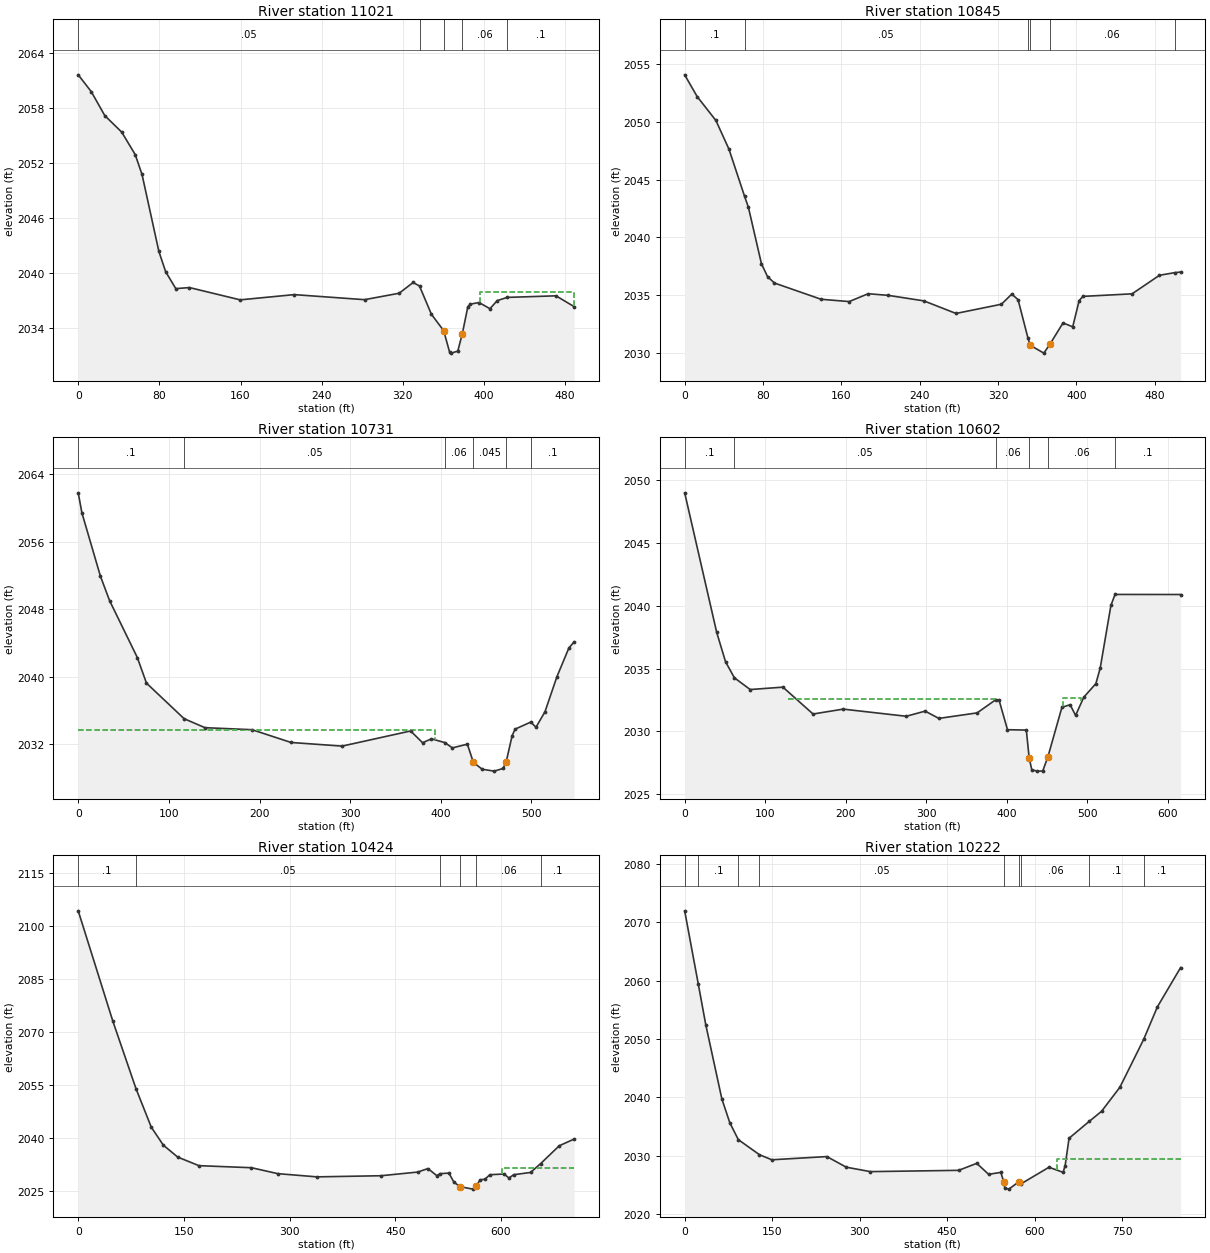
Type RM Length L Ch R = 1 ,11021   ,176,176,176
XS GIS Cut Line= 3
2199178.75386905326963.9460828432199497.56029411 327022.04828093
2199647.60166402327090.142041984
#Sta/Elev= 30
       0 2061.59    12.8 2059.77    26.2 2057.15    42.9 2055.35    56.2  2052.9
    62.9 2050.74    79.5 2042.36    86.2 2040.15    96.2 2038.31   109.6 2038.43
   159.6 2037.09   212.9 2037.66   282.2 2037.11   316.3 2037.81   330.1 2038.98
  336.392038.597   348.1 2035.52   360.22033.738   366.1 2031.38   367.7 2031.29
   374.1 2031.51   378.62033.412     384 2036.34   386.4 2036.62     395  2036.8
   405.8 2036.13     413 2037.01  422.862037.358   470.9 2037.53   488.8 2036.35
#Mann= 5 ,-1 , 0
       0     .05       0  336.39     .06       0   360.2    .045       0
   378.6     .06       0  422.86      .1       0
#XS Ineff= 2 , 0
                          395.53         2037.93
Permanent Ineff=
       F       F
Bank Sta=360.2,378.6
XS Rating Curve= 0 ,0
Exp/Cntr(USF)=0,0
Exp/Cntr=0.3,0.1

Type RM Length L Ch R = 1 ,10845   ,113.9,113.9,113.9
XS GIS Cut Line= 3
2199113.93465384327148.999904497  2199444.160008327199.629421038
2199616.50263042327203.723191085
#Sta/Elev= 30
       0  2054.1    12.7 2052.22    31.9 2050.14    45.2 2047.66    61.22043.559
    65.1 2042.61    78.4 2037.72    84.6 2036.61    91.6 2036.05   139.3 2034.64
     168 2034.44   187.4 2035.12   207.8 2034.98   244.3  2034.5   277.1 2033.41
   323.5 2034.21   334.1 2035.09   340.5  2034.6  350.542031.296   352.9 2030.65
   366.8 2029.97     373 2030.74   386.4 2032.59   396.3 2032.25   402.9 2034.53
   406.7 2034.89   456.9 2035.11   484.9 2036.72  500.322036.945   506.5    2037
#Mann= 6 ,-1 , 0
       0      .1       0    61.2     .05       0  350.54     .06       0
   352.9    .045       0     373     .06       0  500.32      .1       0
#XS Ineff= 2 , 0
          334.12 2035.02
Permanent Ineff=
       F       F
Bank Sta=352.9,373
XS Rating Curve= 0 ,0
Exp/Cntr(USF)=0,0
Exp/Cntr=0.3,0.1

Type RM Length L Ch R = 1 ,10731   ,129.5,129.5,129.5
XS GIS Cut Line= 3
2199039.76664774327232.0346415152199383.32902171327322.047058049
2199574.50137995 327304.89653733
#Sta/Elev= 30
       0 2061.76     4.1 2059.38    24.5  2051.9    34.6 2049.01    65.2 2042.28
    75.3 2039.25  116.822035.042   139.8 2033.98   191.8 2033.74   234.8 2032.23
   291.1  2031.8   366.7 2033.59   379.9  2032.2   389.7 2032.66  404.472032.214
   412.8 2031.59   429.3 2032.03   435.9 2029.88   445.7 2029.06   458.9 2028.84
   468.8 2029.16   472.1 2029.93   478.7 2033.04     482 2033.81  499.262034.643
     505 2034.03   514.9 2035.86   528.1 2040.01   541.3 2043.41   547.1 2044.13
#Mann= 6 ,-1 , 0
       0      .1       0  116.82     .05       0  404.47     .06       0
   435.9    .045       0   472.1     .06       0  499.26      .1       0
#XS Ineff= 2 , 0
          393.94 2033.73
Permanent Ineff=
       F       F
Bank Sta=435.9,472.1
XS Rating Curve= 0 ,0
Exp/Cntr(USF)=0,0
Exp/Cntr=0.3,0.1

Type RM Length L Ch R = 1 ,10602   ,177.9,177.9,177.9
XS GIS Cut Line= 2
2199034.09940997327322.4567502382199629.05725922327482.832564278
#Sta/Elev= 30
       0    2049    39.8 2037.88    50.8 2035.54    61.82034.263    81.4 2033.33
   122.1 2033.52   159.5 2031.38   196.9 2031.77   275.3  2031.2   298.8 2031.61
   315.8 2031.03   363.4 2031.47  386.422032.515   390.6 2032.49   401.1 2030.13
   424.5  2030.1     428  2027.9   431.3 2026.93   438.1 2026.83   444.9 2026.84
   451.3 2027.97   468.7 2031.91   478.9 2032.12   485.7 2031.27   495.9 2032.72
   510.9  2033.8   516.3 2035.04   529.6 2040.03  534.692040.905   616.2  2040.9
#Mann= 6 ,-1 , 0
       0      .1       0    61.8     .05       0  386.42     .06       0
     428    .045       0   451.3     .06       0  534.69      .1       0
#XS Ineff= 2 ,-1
  128.92  387.82 2032.58  469.68   492.52032.676
Permanent Ineff=
       F       F
Bank Sta=428,451.3
XS Rating Curve= 0 ,0
Exp/Cntr(USF)=0,0
Exp/Cntr=0.3,0.1

Type RM Length L Ch R = 1 ,10424   ,201.9,201.9,201.9
XS GIS Cut Line= 2
2198871.64410997327457.1702761692199549.57391319327646.110205511
#Sta/Elev= 30
       0 2104.32    49.2 2073.06   82.052053.965   103.7 2043.09   120.8 2038.01
   141.2 2034.63   171.3  2032.2   245.9 2031.62   283.2 2029.94   338.7 2029.03
   429.7 2029.35   481.8 2030.39   496.3 2031.38     509 2029.36  513.222029.927
   526.1  2030.1   532.9 2027.61   541.6 2026.27   560.1 2025.56   564.7 2026.37
   570.3 2028.19   577.2 2028.37   584.2 2029.64   604.4 2029.84   611.2 2028.71
     618 2029.64   641.9 2030.28  656.092032.759   682.7 2037.84   703.8 2039.73
#Mann= 6 ,-1 , 0
       0      .1       0   82.05     .05       0  513.22     .06       0
   541.6    .045       0   564.7     .06       0  656.09      .1       0
#XS Ineff= 2 , 0
          495.62 2031.19  601.31          2031.4
Permanent Ineff=
       F       F
Bank Sta=541.6,564.7
XS Rating Curve= 0 ,0
Exp/Cntr(USF)=0,0
Exp/Cntr=0.3,0.1

Type RM Length L Ch R = 1 ,10222   ,235.2,235.2,235.2
XS GIS Cut Line= 2
2198789.46837493327618.4898446772199600.07497417327874.257202369
#Sta/Elev= 30
       0 2071.95   23.272059.431    36.1 2052.45    63.7 2039.72    77.4 2035.61
   91.932032.733  128.152030.151   149.4 2029.28   243.7 2029.83     277 2028.01
   318.2 2027.25   469.6 2027.47   500.6 2028.67   520.9 2026.79   541.9 2027.12
   546.9 2025.47   548.7 2024.43   555.6 2024.25   572.8 2025.51  576.952025.186
   624.4    2028   648.5 2027.13     652 2028.23   658.8 2032.97  693.582035.879
   714.5 2037.59   745.9 2041.71  786.582049.896   810.2 2055.49     850 2062.23
#Mann= 9 ,-1 , 0
       0      .1       0   23.27      .1       0   91.93      .1       0
  128.15     .05       0   546.9    .045       0   572.8     .05       0
  576.95     .06       0  693.58      .1       0  786.58      .1       0
#XS Ineff= 2 , 0
          498.36 2028.32  637.93         2029.41
Permanent Ineff=
       F       F
Bank Sta=546.9,572.8
XS Rating Curve= 0 ,0
Exp/Cntr(USF)=0,0
Exp/Cntr=0.3,0.1

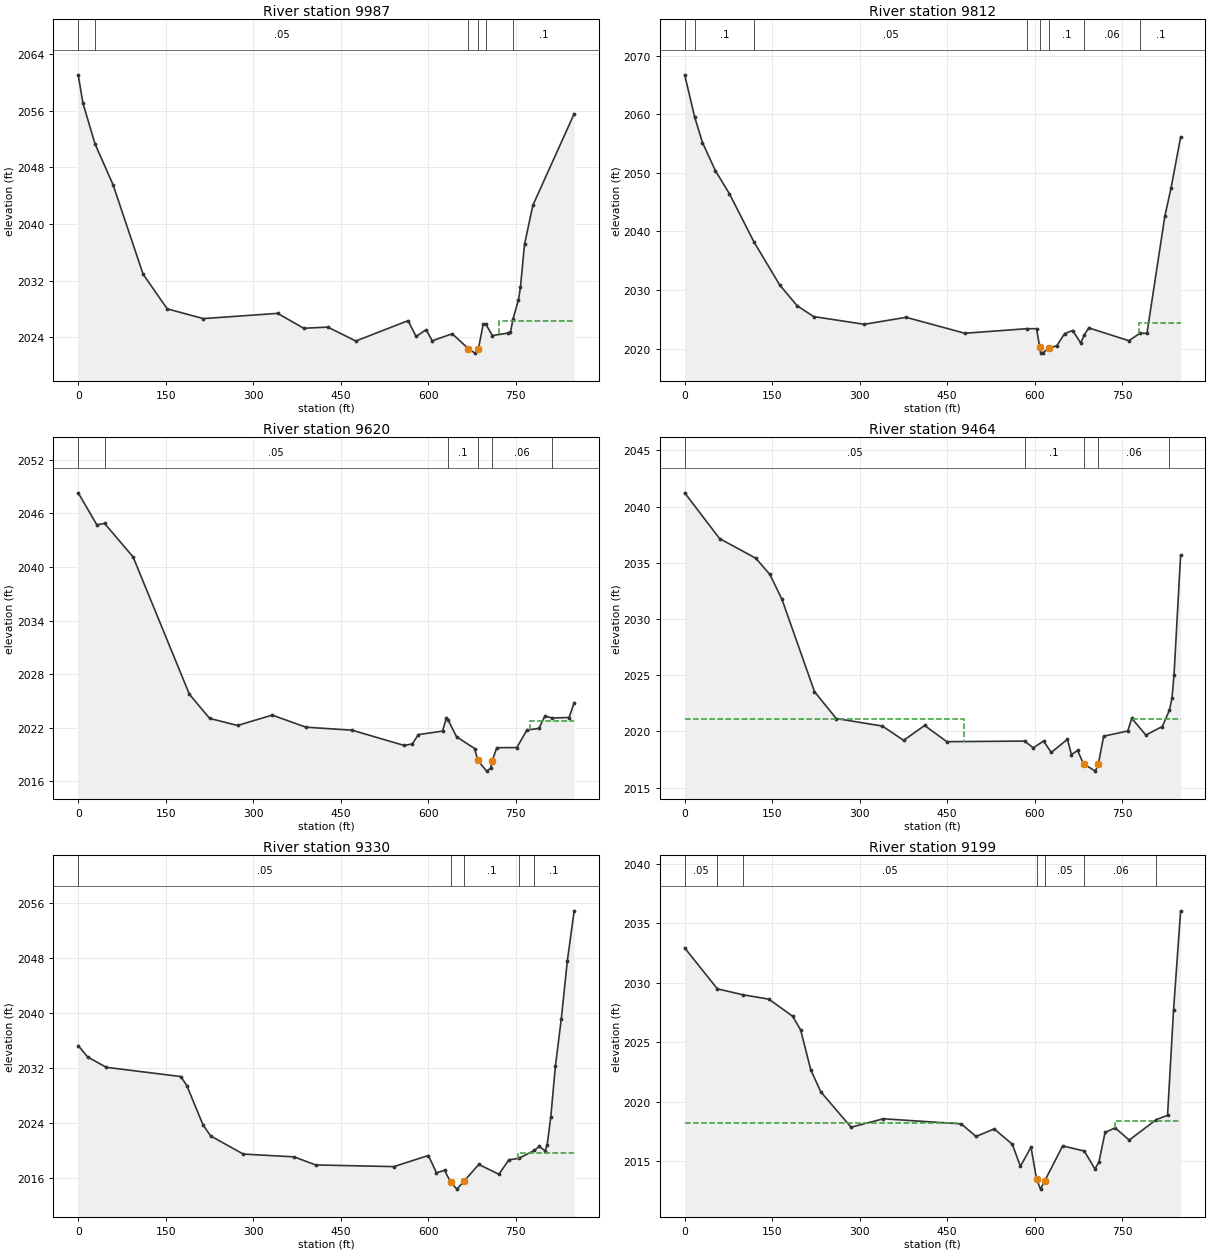
Type RM Length L Ch R = 1 ,9987    ,174.7,174.7,174.7
XS GIS Cut Line= 2
2198681.76191055327808.887792155 2199492.3685098328064.655149846
#Sta/Elev= 30
       0 2061.05       8 2057.09   28.832051.295    59.6 2045.57   111.2 2032.93
   152.5 2028.04   214.4 2026.66   341.7  2027.4   386.5  2025.3   427.8 2025.46
   475.8  2023.5   565.4 2026.37   579.1 2024.14   596.3  2025.1   606.7 2023.53
     641 2024.52   668.6 2022.43   679.9 2021.79   685.8 2022.35   694.2 2025.91
  698.682025.864   709.9 2024.27   737.4 2024.63   740.8  2024.7  745.432026.667
   754.6 2029.31     758 2031.11   764.9 2037.12   779.3 2042.66     850 2055.55
#Mann= 6 ,-1 , 0
       0      .1       0   28.83     .05       0   668.6    .045       0
   685.8     .05       0  698.68     .06       0  745.43      .1       0
#XS Ineff= 2 , 0
          564.89 2026.29  721.34         2026.37
Permanent Ineff=
       F       F
Bank Sta=668.6,685.8
XS Rating Curve= 0 ,0
Exp/Cntr(USF)=0,0
Exp/Cntr=0.3,0.1

Type RM Length L Ch R = 1 ,9812    ,192,192,192
XS GIS Cut Line= 2
2198606.42426303327934.5909482332199417.03086227328190.358305925
#Sta/Elev= 30
       0 2066.73   17.282059.467    30.5 2055.18    52.6 2050.38    76.7 2046.44
  118.942038.181   162.7  2030.9   192.6 2027.34   220.9 2025.48   307.7 2024.16
   379.5 2025.35   480.3 2022.63  586.222023.409   603.1 2023.41   608.4 2020.33
     610 2019.31   613.4 2019.24     6252020.181   637.5 2020.46   651.2 2022.58
     665  2023.1   678.8 2020.97  684.53 2022.28   692.5 2023.55   761.3 2021.36
  780.262022.627   792.3 2022.61   822.9 2042.56   833.6 2047.43     850 2056.08
#Mann= 8 ,-1 , 0
       0      .1       0   17.28      .1       0  118.94     .05       0
  586.22      .1       0   608.4    .045       0     625      .1       0
  684.53     .06       0  780.26      .1       0
#XS Ineff= 2 , 0
                          778.86         2024.37
Permanent Ineff=
       F       F
Bank Sta=608.4,625
XS Rating Curve= 0 ,0
Exp/Cntr(USF)=0,0
Exp/Cntr=0.3,0.1

Type RM Length L Ch R = 1 ,9620    ,155.4,155.4,155.4
XS GIS Cut Line= 2
2198576.80056896 328083.540466492199386.69771526328341.534941304
#Sta/Elev= 30
       0 2048.31    31.9 2044.73    45.22044.887    94.1 2041.13   190.5 2025.77
   225.3 2023.06   273.1 2022.27   332.4 2023.43   390.2 2022.08   469.4 2021.74
   558.9 2020.03   572.6 2020.21     583 2021.25   624.4 2021.64   631.2 2023.15
  633.652022.925   648.5    2021   679.5 2019.69   684.9 2018.35   700.1 2017.16
     707 2017.49   709.3 2018.26   717.3 2019.78   751.8  2019.8     769 2021.76
   789.6 2021.94   799.8 2023.32  812.282023.113   841.3 2023.16     850 2024.82
#Mann= 6 ,-1 , 0
       0      .1       0    45.2     .05       0  633.65      .1       0
   684.9    .045       0   709.3     .06       0  812.28      .1       0
#XS Ineff= 2 , 0
                          773.64        2022.725
Permanent Ineff=
       F       F
Bank Sta=684.9,709.3
XS Rating Curve= 0 ,0
Exp/Cntr=0.3,0.1

Type RM Length L Ch R = 1 ,9464    ,134.9,134.9,134.9
XS GIS Cut Line= 2
2198547.17687488328232.4899847462199356.36456824328492.711576684
#Sta/Elev= 30
       0 2041.22    59.8 2037.15   121.9  2035.4     146 2033.96   166.7 2031.75
   222.5 2023.53   259.7 2021.14   338.8 2020.47   375.3  2019.2   411.3 2020.52
   449.3 2019.08  582.632019.133   597.4 2018.53   615.2 2019.14   628.2 2018.12
     656 2019.29   662.9 2017.93   673.3  2018.3   683.6 2017.11   703.8 2016.46
   709.1 2017.13   718.1 2019.57   759.4 2020.03   766.3 2021.16   790.4 2019.67
   818.6 2020.43  830.852021.883   835.2 2022.94   838.7 2025.02     850 2035.68
#Mann= 5 ,-1 , 0
       0     .05       0  582.63      .1       0   683.6    .045       0
   709.1     .06       0  830.85      .1       0
#XS Ineff= 2 , 0
          479.23 2021.12  768.42         2021.08
Permanent Ineff=
       F       F
Bank Sta=683.6,709.1
XS Rating Curve= 0 ,0
Exp/Cntr(USF)=0,0
Exp/Cntr=0.3,0.1

Type RM Length L Ch R = 1 ,9330    ,130.6,130.6,130.6
XS GIS Cut Line= 2
2198512.41489166328348.279705324 2199320.6145139328611.534701048
#Sta/Elev= 30
       0 2035.26    16.2 2033.61    48.1 2032.11   175.8 2030.77   186.2 2029.45
   213.8 2023.77     227 2022.15   282.8 2019.52   370.1 2019.11     407 2017.94
   540.9  2017.7   600.2 2019.31     614  2016.8   627.8 2017.16   638.2 2015.47
   648.9 2014.43   661.6 2015.62   686.5 2018.01     721 2016.59   738.2 2018.69
  754.942018.886  781.732020.044     790 2020.62   800.4 2019.99   803.8 2020.89
     810 2024.94   817.8 2032.23     828 2039.18   838.3 2047.55     850 2054.82
#Mann= 5 ,-1 , 0
       0     .05       0   638.2    .045       0   661.6      .1       0
  754.94     .06       0  781.73      .1       0
#XS Ineff= 2 , 0
                           753.2         2019.71
Permanent Ineff=
       F       F
Bank Sta=638.2,661.6
XS Rating Curve= 0 ,0
Exp/Cntr=0.3,0.1

Type RM Length L Ch R = 1 ,9199    ,151.3,151.3,151.3
XS GIS Cut Line= 2
2198477.65290843328464.0694259012199284.86445956328730.357825412
#Sta/Elev= 30
       0 2032.94   56.022029.496    99.82028.995   144.2 2028.63     185 2027.19
   198.8 2026.03   216.1 2022.68   233.4 2020.82   285.2 2017.85   340.5 2018.56
   474.1 2018.13   499.4 2017.07   530.5 2017.71   561.6 2016.41   575.4 2014.56
   593.6 2016.18     603 2013.49   609.9 2012.64   617.12013.334   647.9 2016.28
  684.972015.843   703.2 2014.33   710.1 2014.94   720.5 2017.41   737.8 2017.79
   761.9 2016.77  808.432018.495   827.6 2018.85   837.9 2027.73     850 2036.06
#Mann= 7 ,-1 , 0
       0     .05       0   56.02      .1       0    99.8     .05       0
     603    .045       0   617.1     .05       0  684.97     .06       0
  808.43      .1       0
#XS Ineff= 2 , 0
          466.81  2018.2  737.98         2018.34
Permanent Ineff=
       F       F
Bank Sta=603,617.1
XS Rating Curve= 0 ,0
Exp/Cntr(USF)=0,0
Exp/Cntr=0.3,0.1

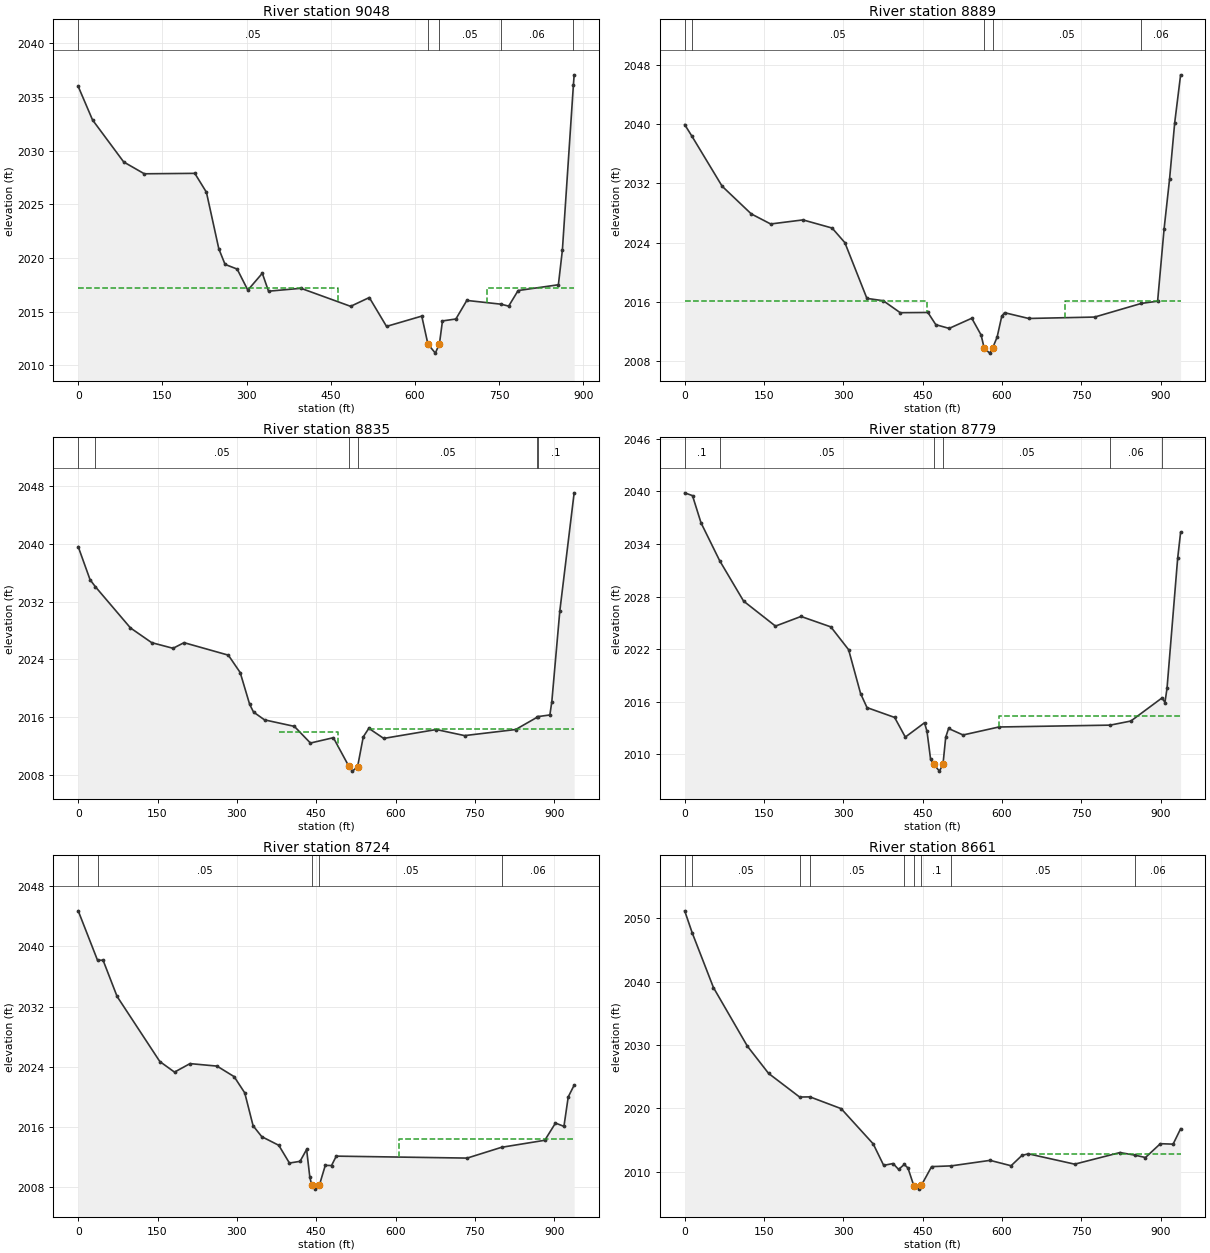
Type RM Length L Ch R = 1 ,9048    ,158.1,158.1,158.1
XS GIS Cut Line= 2
2198443.63841707 328505.341892152199229.54267183328909.963914177
#Sta/Elev= 30
       0 2035.98    25.5 2032.86    81.1 2028.94   117.8 2027.84   207.8 2027.88
   228.5 2026.12   250.6 2020.85   261.7  2019.4   283.3 2018.96   302.3    2017
   328.1 2018.57   339.2  2016.9     397 2017.17   485.5 2015.49   518.8 2016.31
   549.5 2013.62   612.3 2014.58   623.3 2011.97   636.5 2011.13   643.8    2012
   649.2 2014.13   673.1 2014.31   692.6 2016.04  753.52 2015.69   767.2 2015.51
     784 2016.96   855.8  2017.5   862.9 2020.71  882.522036.088   883.9 2037.06
#Mann= 5 ,-1 , 0
       0     .05       0   623.3    .045       0   643.8     .05       0
  753.52     .06       0  882.52      .1       0
#XS Ineff= 2 , 0
          462.872017.185 728.185        2017.215
Permanent Ineff=
       F       F
Bank Sta=623.3,643.8
XS Rating Curve= 0 ,0
Exp/Cntr=0.3,0.1

Type RM Length L Ch R = 1 ,8889    ,54.7,54.7,54.7
XS GIS Cut Line= 2
2198409.62392572  328546.6143584 2199174.2208841329089.570002942
#Sta/Elev= 30
       0 2039.95   13.652038.389    70.8 2031.63   125.9 2027.89   162.6 2026.53
   223.7 2027.08   278.8 2025.98   302.9 2024.01   344.6 2016.48   375.4 2016.17
   407.6 2014.55   459.9 2014.58   474.9 2012.93   500.1 2012.43   542.9  2013.8
   560.5 2011.54   566.32009.792   576.6 2009.09   582.22009.762   590.8 2011.25
   599.6 2014.08   604.9 2014.55   650.5 2013.77   775.2 2013.96  863.762015.808
   894.3  2016.1   906.5 2025.83   916.9 2032.59   926.6 2040.19   937.8 2046.67
#Mann= 5 ,-1 , 0
       0      .1       0   13.65     .05       0   566.3    .045       0
   582.2     .05       0  863.76     .06       0
#XS Ineff= 2 , 0
          458.93 2016.17  718.39         2016.09
Permanent Ineff=
       F       F
Bank Sta=566.3,582.2
XS Rating Curve= 0 ,0
Exp/Cntr(USF)=0,0
Exp/Cntr=0.5,0.3

Type RM Length L Ch R = 1 ,8835    ,55.4,55.4,55.4
XS GIS Cut Line= 2
2198405.43863751328603.4093619612199170.03559588329146.365006503
#Sta/Elev= 30
       0  2039.6    22.4 2035.03   32.222034.078    98.8 2028.35     139 2026.31
   179.3 2025.53   200.1 2026.31   283.9 2024.58   306.3 2022.17   324.2 2017.77
   331.5  2016.7   352.3 2015.62   408.7 2014.72   439.1 2012.41   482.5 2013.15
   511.92009.175   518.5 2008.52   528.32009.137     539 2013.26   549.5 2014.45
   577.7 2013.05   677.1 2014.28   730.6 2013.44   827.2 2014.28  868.112015.994
  869.142016.068   891.9  2016.3   895.6 2018.16   910.7  2030.7   937.8 2047.06
#Mann= 6 ,-1 , 0
       0      .1       0   32.22     .05       0   511.9    .045       0
   528.3     .05       0  868.11     .06       0  869.14      .1       0
#XS Ineff= 2 ,-1
     379  491.63 2013.94  548.93   937.8 2014.39
Permanent Ineff=
       F       F
Bank Sta=511.9,528.3
XS Rating Curve= 0 ,0
Exp/Cntr(USF)=0,0
Exp/Cntr=0.5,0.3

Type RM Length L Ch R = 1 ,8779    ,55.6,55.6,55.6
XS GIS Cut Line= 2
2198388.64559601328650.7806479152199153.24255438329193.736292457
#Sta/Elev= 30
       0 2039.82    14.8  2039.5    30.9  2036.4   66.152032.087   111.4 2027.48
   171.7 2024.63     220 2025.73   276.4 2024.54     310 2021.94   332.7 2016.93
   344.8 2015.34     397 2014.22   417.2 2011.98   453.5 2013.61   458.2 2012.64
     465 2009.46   470.6 2008.91   481.7  2008.1   488.4 2008.86   493.6 2011.96
     499 2012.96   526.4 2012.22   594.2 2013.13  804.712013.343   843.7 2013.81
  903.082016.463   908.1 2015.91   912.1 2017.54   932.2 2032.35   937.8 2035.32
#Mann= 6 ,-1 , 0
       0      .1       0   66.15     .05       0   470.6    .045       0
   488.4     .05       0  804.71     .06       0  903.08      .1       0
#XS Ineff= 2 , 0
                          594.82         2014.44
Permanent Ineff=
       F       F
Bank Sta=470.6,488.4
XS Rating Curve= 0 ,0
Exp/Cntr(USF)=0,0
Exp/Cntr=0.5,0.3

Type RM Length L Ch R = 1 ,8724    ,62.7,62.7,62.7
XS GIS Cut Line= 2
2198370.31969885 328702.475947712199134.91665723329245.431592251
#Sta/Elev= 30
       0 2044.74   36.532038.161      47 2038.17    73.5 2033.35   154.3 2024.69
   182.1 2023.28   211.4 2024.41   262.5 2024.08   294.8 2022.68   314.9 2020.52
   330.7 2016.14   347.1 2014.69   379.3 2013.54   399.4 2011.18   419.5 2011.41
   431.9 2012.99     438 2009.28   441.72008.225   447.7 2007.71   455.9 2008.21
   467.2 2010.87     479 2010.85     488  2012.1   735.5 2011.84  800.622013.277
   882.3 2014.21   902.5  2016.5   918.5 2016.06   926.6 2019.98   937.8 2021.54
#Mann= 5 ,-1 , 0
       0      .1       0   36.53     .05       0   441.7    .045       0
   455.9     .05       0  800.62     .06       0
#XS Ineff= 2 , 0
                          607.36         2014.32
Permanent Ineff=
       F       F
Bank Sta=441.7,455.9
XS Rating Curve= 0 ,0
Exp/Cntr(USF)=0,0
Exp/Cntr=0.3,0.1

Type RM Length L Ch R = 1 ,8661    ,189.4,189.4,189.4
XS GIS Cut Line= 2
2198343.20845769328759.5066223372199107.80541607329302.462266879
#Sta/Elev= 30
       0 2051.19    14.12047.745    54.4 2039.08   118.5 2029.84   158.7 2025.53
  217.372021.802  236.89 2021.83   295.9 2019.97   356.5 2014.41   376.3 2011.02
     394 2011.31   404.5 2010.38  415.21 2011.16   422.2 2010.61   433.32007.801
   443.4 2007.27   447.5 2007.86   466.9 2010.82  504.08 2010.94   577.5 2011.81
   617.2 2010.96   637.9  2012.6     650 2012.84   737.5 2011.21     823 2013.04
  851.022012.637   871.3 2012.26   899.5 2014.44   923.6 2014.37   937.8  2016.8
#Mann= 9 ,-1 , 0
       0      .1       0    14.1     .05       0  217.37      .1       0
  236.89     .05       0  415.21      .1       0   433.3    .045       0
   447.5      .1       0  504.08     .05       0  851.02     .06       0
#XS Ineff= 2 , 0
                          654.21         2012.87
Permanent Ineff=
       F       F
Bank Sta=433.3,447.5
XS Rating Curve= 0 ,0
Exp/Cntr(USF)=0,0
Exp/Cntr=0.3,0.1

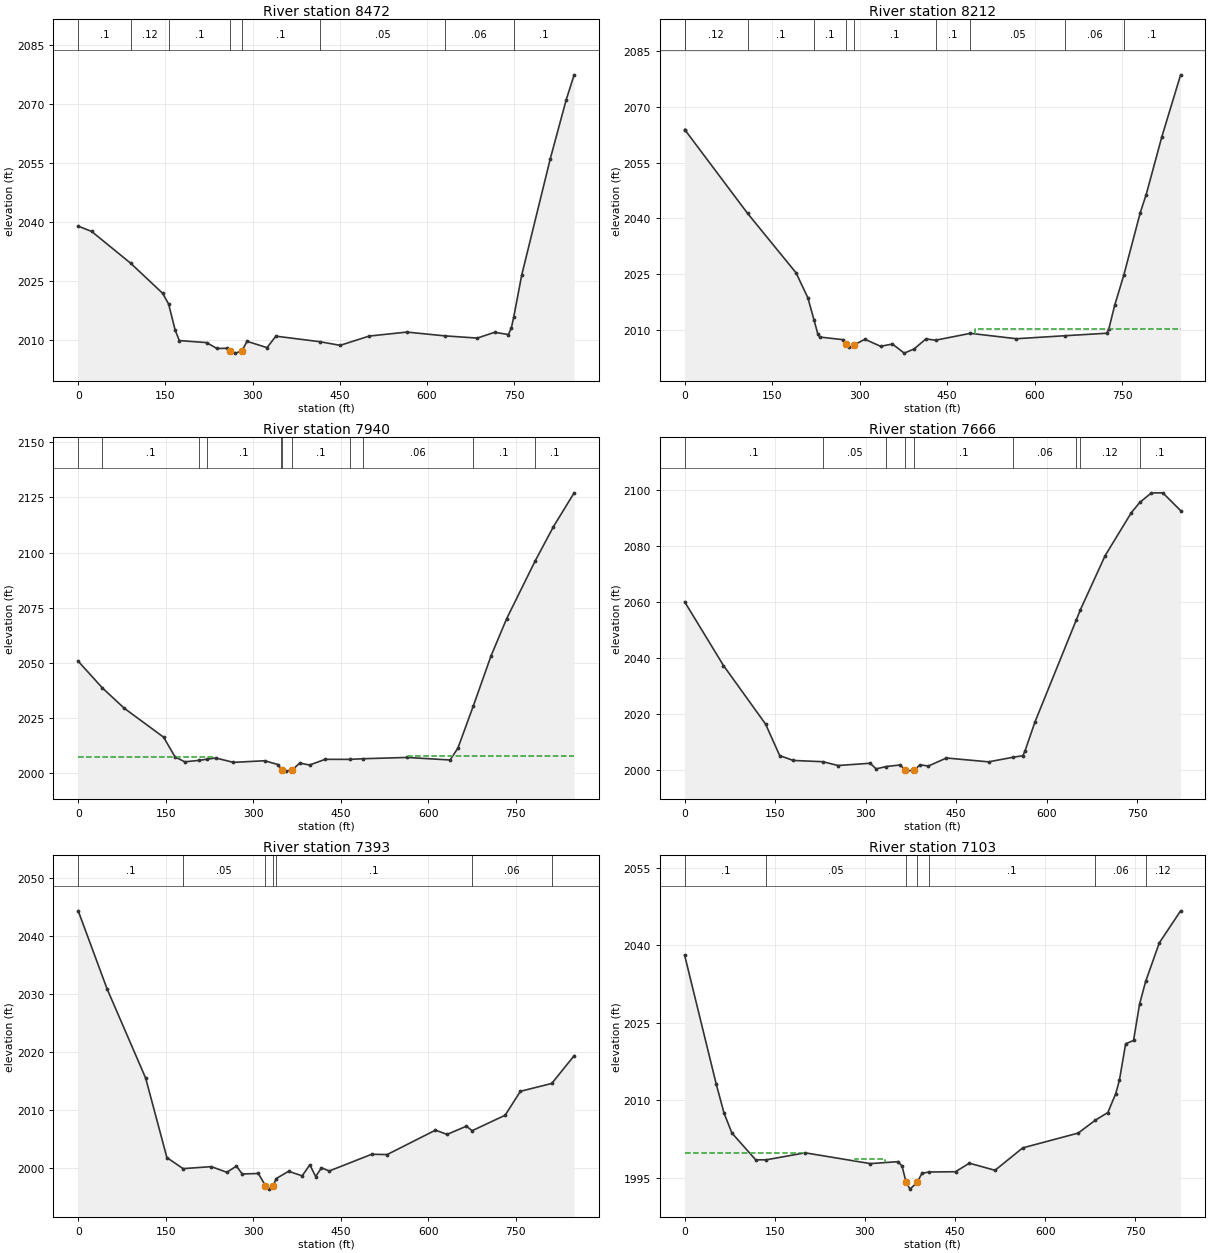
Type RM Length L Ch R = 1 ,8472    ,260.1,260.1,260.1
XS GIS Cut Line= 2
2198373.05943708329072.9622572192199152.36738363329419.923708204
#Sta/Elev= 30
       0 2038.97    23.1 2037.62   90.422029.499   145.2 2021.87  155.512019.138
   166.7 2012.52   173.9 2009.83   220.8 2009.31   238.6 2007.81   256.5 2007.86
   261.1 2007.15   270.4 2006.63   281.7  2007.2   290.3 2009.64   324.8 2008.03
     340 2010.95  416.132009.529   450.5 2008.61   500.7 2010.98   565.4 2011.99
   630.4 2011.03   686.5 2010.46   716.2 2011.93     740 2011.37     745 2013.01
  749.132015.781   762.9  2026.5   812.1 2056.16   839.4 2071.13   853.1  2077.5
#Mann= 8 ,-1 , 0
       0      .1       0   90.42     .12       0  155.51      .1       0
   261.1    .045       0   281.7      .1       0  416.13     .05       0
   630.4     .06       0  749.13      .1       0
#XS Ineff= 2 , 0
                           566.9         2011.92
Permanent Ineff=
       F       F
Bank Sta=261.1,281.7
XS Rating Curve= 0 ,0
Exp/Cntr(USF)=0,0
Exp/Cntr=0.3,0.1

Type RM Length L Ch R = 1 ,8212    ,271.9,271.9,271.9
XS GIS Cut Line= 2
2198247.70451882329350.3902816422199075.05209391329545.315882814
#Sta/Elev= 30
       0 2063.93      .32063.859  107.792041.342   190.9 2025.32   211.1 2018.62
  221.852012.509     228 2008.97   231.4 2008.03   271.8  2007.3   276.12006.139
   281.9 2005.26   290.12005.888   308.9 2007.42   335.8 2005.53   356.1 2006.14
   376.3 2003.69   393.1  2004.8   413.4 2007.51  430.272007.181  489.64 2009.02
   568.6 2007.57  651.82 2008.38   723.5 2009.05   726.9 2010.16     737 2016.58
  752.742024.772   780.8 2041.51   790.9 2046.36   817.8 2061.96     850 2078.66
#Mann= 10 ,-1 , 0
       0      .1       0      .3     .12       0  107.79      .1       0
  221.85      .1       0   276.1    .045       0   290.1      .1       0
  430.27      .1       0  489.64     .05       0  651.82     .06       0
  752.74      .1       0
#XS Ineff= 2 , 0
                          497.81         2010.26
Permanent Ineff=
       F       F
Bank Sta=276.1,290.1
XS Rating Curve= 0 ,0
Exp/Cntr(USF)=0,0
Exp/Cntr=0.3,0.1

Type RM Length L Ch R = 1 ,7940    ,274.1,274.1,274.1
XS GIS Cut Line= 2
2198241.37527347329551.6730020132199075.24410548329716.484321437
#Sta/Elev= 30
       0 2050.77   41.35  2038.7    78.8  2029.5   146.3 2016.37   165.8 2007.51
   182.5  2005.2  207.652005.872  221.062006.398     236 2006.92   266.1 2004.95
   319.6 2005.69     343 2003.91  347.742001.893   348.72001.658   356.4 2000.98
   367.2 2001.65   379.8 2004.63   396.5 2003.75   423.3 2006.33  465.242006.302
  488.292006.604   563.7 2007.18   637.3 2006.03   650.7 2011.38  677.182030.513
   707.5 2053.16   734.3 2070.05  783.152096.189   814.6  2111.8     850 2127.07
#Mann= 11 ,-1 , 0
       0      .1       0   41.35      .1       0  207.65      .1       0
  221.06      .1       0  347.74      .1       0   348.7    .045       0
   367.2      .1       0  465.24     .05       0  488.29     .06       0
  677.18      .1       0  783.15      .1       0
#XS Ineff= 2 , 0
          234.83 2007.48  565.16         2007.69
Permanent Ineff=
       F       F
Bank Sta=348.7,367.2
XS Rating Curve= 0 ,0
Exp/Cntr(USF)=0,0
Exp/Cntr=0.3,0.1

Type RM Length L Ch R = 1 ,7666    ,272.8,272.8,272.8
XS GIS Cut Line= 2
2198206.07029358329825.4710918112199016.18459316329964.159489866
#Sta/Elev= 30
       0 2060.12    64.3 2037.42   134.2 2016.49   157.5 2005.28     180 2003.56
  229.182003.106   254.1 2001.75   307.3 2002.56   317.3 2000.55  334.192001.395
   357.2 2001.96     3652000.177   367.2 1999.75   380.5 2000.18   390.3 2002.01
   403.8 2001.56   433.8 2004.43   503.7 2003.06   544.22004.701   560.3 2005.25
   563.7 2006.78   580.7 2017.39  649.212053.791  655.932057.376   696.8 2076.61
   740.2 2091.93  754.222095.586   773.3 2098.97   792.4 2099.01   821.9 2092.67
#Mann= 9 ,-1 , 0
       0      .1       0  229.18     .05       0  334.19      .1       0
     365    .045       0   380.5      .1       0   544.2     .06       0
  649.21      .1       0  655.93     .12       0  754.22      .1       0
#XS Ineff= 2 , 0
                          443.32         2003.69
Permanent Ineff=
       F       F
Bank Sta=365,380.5
XS Rating Curve= 0 ,0
Exp/Cntr(USF)=0,0
Exp/Cntr=0.3,0.1

Type RM Length L Ch R = 1 ,7393    ,290.1,290.1,290.1
XS GIS Cut Line= 2
 2198187.8219085330102.6219572042199029.84208823330218.820136741
#Sta/Elev= 30
       0 2044.28    49.3 2030.89   115.6 2015.49     152 2001.81  179.711999.909
   228.2 2000.25   254.7 1999.28   271.2 2000.34   281.1 1998.99   308.7 1999.07
   320.9 1996.98   327.5 1996.38   334.1 1996.97  339.32  1998.2   360.6 1999.45
   383.8 1998.67     397 2000.56     407 1998.55   416.9 2000.05   430.2  1999.5
     503 2002.38   529.5 2002.33   612.3 2006.53   632.2  2005.8   665.3 2007.21
  675.212006.436   731.7  2009.1   757.9 2013.22  811.582014.566     850 2019.35
#Mann= 7 ,-1 , 0
       0      .1       0  179.71     .05       0   320.9    .045       0
   334.1     .05       0  339.32      .1       0  675.21     .06       0
  811.58      .1       0
Bank Sta=320.9,334.1
XS Rating Curve= 0 ,0
Exp/Cntr(USF)=0,0
Exp/Cntr=0.3,0.1

Type RM Length L Ch R = 1 ,7103    ,211.6,211.6,211.6
XS GIS Cut Line= 2
2198148.46249869330411.4576189042198970.84170841330342.411093801
#Sta/Elev= 30
       0 2038.07    52.3 2013.24    65.5 2007.53    78.6 2003.67   118.2 1998.48
  135.721998.485   200.5 1999.84   309.1 1997.75   355.2 1998.13   361.8 1997.24
   368.4 1994.19     375 1992.81   386.8 1994.11   394.7 1995.84  406.021996.127
   450.7 1996.18   473.7 1997.83   516.5 1996.46   562.6  2000.8   654.8 2003.66
  683.542006.171   704.2 2007.64   717.4 2011.32   723.5 2013.93   733.8 2020.94
     747  2021.6   756.9 2028.58  767.082033.018   789.8 2040.48   825.3 2046.69
#Mann= 7 ,-1 , 0
       0      .1       0  135.72     .05       0   368.4    .045       0
   386.8     .05       0  406.02      .1       0  683.54     .06       0
  767.08     .12       0
#XS Ineff= 2 ,-1
       0  202.87 1999.85  283.94  333.491998.583
Permanent Ineff=
       F       F
Bank Sta=368.4,386.8
XS Rating Curve= 0 ,0
Exp/Cntr(USF)=0,0
Exp/Cntr=0.3,0.1

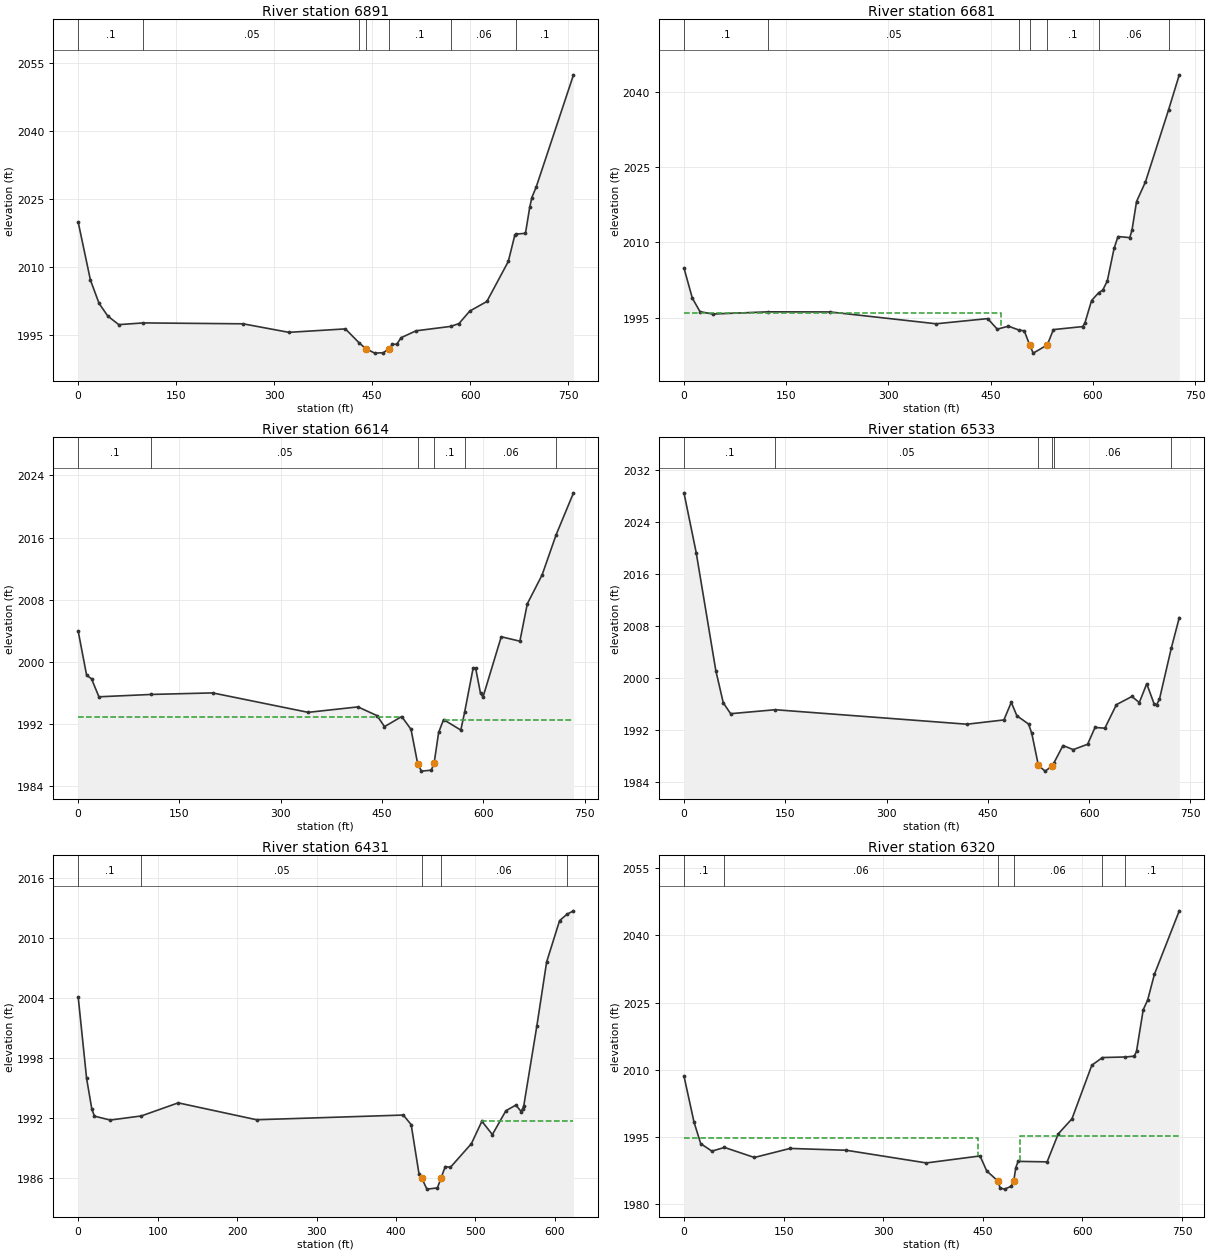
Type RM Length L Ch R = 1 ,6891    ,210.1,210.1,210.1
XS GIS Cut Line= 3
2198182.20187643330484.3201717192198568.74487465330556.208274404
2198933.52697915330556.115848622
#Sta/Elev= 30
       0 2019.96    18.7  2007.2      32 2002.03    45.4 1999.24    62.1 1997.36
   99.751997.737   252.3 1997.54   322.4 1995.66   408.9 1996.42  430.241993.304
   440.7 1992.01   453.9 1991.08     467 1991.17   475.4 1992.04     481 1992.99
   487.6 1993.07   494.2 1994.48   517.1    1996  569.921996.966   582.7 1997.59
   599.2 2000.34   625.4 2002.46   658.2 2011.27   668.1 2017.02  670.542017.314
   684.5 2017.48     691  2023.2   694.3 2025.37   700.9 2027.67     758  2052.4
#Mann= 7 ,-1 , 0
       0      .1       0   99.75     .05       0  430.24      .1       0
   440.7    .045       0   475.4      .1       0  569.92     .06       0
  670.54      .1       0
Bank Sta=440.7,475.4
XS Rating Curve= 0 ,0
Exp/Cntr=0.3,0.1

Type RM Length L Ch R = 1 ,6681    ,67.3,67.3,67.3
XS GIS Cut Line= 3
2198215.94125417330557.1827245342198554.75987195330737.419790183
2198896.21224989330769.820603443
#Sta/Elev= 30
       0  2004.9    12.3 1998.89    23.5  1996.2      42 1995.72  123.42 1996.16
   214.2 1996.14   370.1 1993.78   445.7 1994.81   459.7 1992.71   476.2  1993.3
  491.87 1992.51   499.3 1992.38   507.5 1989.49   512.5 1987.93   533.1 1989.56
   542.1 1992.62     585 1993.22   588.3 1993.93   598.1 1998.41  608.361999.947
   614.6 2000.51   621.2 2002.32   631.1 2008.79   636.9 2011.17   654.2 2010.95
   657.5 2012.51   664.1 2018.14   677.2 2022.07  711.022036.392   726.8  2043.4
#Mann= 7 ,-1 , 0
       0      .1       0  123.42     .05       0  491.87      .1       0
   507.5    .045       0   533.1      .1       0  608.36     .06       0
  711.02     .12       0
#XS Ineff= 2 , 0
          465.45 1995.85
Permanent Ineff=
       F       F
Bank Sta=507.5,533.1
XS Rating Curve= 0 ,0
Exp/Cntr(USF)=0,0
Exp/Cntr=0.5,0.3

Type RM Length L Ch R = 1 ,6614    ,80.4,80.4,80.4
XS GIS Cut Line= 2
2198225.43335914330592.3185631242198885.47330692 330912.17365075
#Sta/Elev= 30
       0 2003.98    12.5  1998.3    19.8 1997.84    30.7 1995.53  108.231995.832
   199.1 1996.03   340.6 1993.53   414.3 1994.23   442.7  1993.1   453.6 1991.69
   479.1 1992.99   492.9 1991.34   502.7 1986.95   508.3 1985.97   522.9 1986.09
   527.2 1987.05   533.8 1990.95   541.1  1992.6   566.6 1991.25   572.2 1993.51
   584.9 1999.23   588.5 1999.25   595.8 1995.97   599.5  1995.5   626.5 2003.25
   654.1 2002.68   665.1 2007.49     687  2011.2  707.862016.386   733.5 2021.76
#Mann= 6 ,-1 , 0
       0      .1       0  108.23     .05       0   502.7    .045       0
   527.2      .1       0   572.2     .06       0  707.86      .1       0
#XS Ineff= 2 , 0
          477.11 1992.94  541.98         1992.58
Permanent Ineff=
       F       F
Bank Sta=502.7,527.2
XS Rating Curve= 0 ,0
Exp/Cntr(USF)=0,0
Exp/Cntr=0.5,0.3

Type RM Length L Ch R = 1 ,6533    ,102.6,102.6,102.6
XS GIS Cut Line= 2
2198194.15743891330662.7504681782198854.19738668330982.605555805
#Sta/Elev= 30
       0 2028.53    18.1 2019.34    47.2 2001.16    58.2 1996.22    69.1 1994.54
  135.231995.149   419.1 1992.92   473.8 1993.58   484.7 1996.29     493 1994.22
   510.3 1992.95   515.1  1991.5   524.9 1986.57   534.8  1985.7   545.7 1986.51
  547.731986.942   561.3 1989.64   576.5 1989.01   597.8 1989.84   608.7 1992.42
   623.3 1992.31   640.4 1995.93   663.4 1997.19   674.3 1996.25   685.3 1999.15
   696.2 1996.06   699.8 1995.88   704.2 1996.79  721.642004.616   733.5 2009.32
#Mann= 6 ,-1 , 0
       0      .1       0  135.23     .05       0   524.9    .045       0
   545.7     .05       0  547.73     .06       0  721.64      .1       0
Bank Sta=524.9,545.7
XS Rating Curve= 0 ,0
Exp/Cntr(USF)=0,0
Exp/Cntr=0.5,0.3

Type RM Length L Ch R = 1 ,6431    ,111.2,111.2,111.2
XS GIS Cut Line= 2
2198229.39571128330956.8545106142198850.23503455331013.777873667
#Sta/Elev= 30
       0 2004.14    10.6 1995.98    17.2 1992.91    20.5 1992.21    40.3 1991.82
   79.481992.232   125.9 1993.54   224.5 1991.85   409.2 1992.32   419.1 1991.36
     429 1986.41   432.3 1986.03   438.9 1984.91   452.1 1985.03   456.9 1986.07
     462 1987.17   468.5 1987.09   494.9 1989.46   508.1  1991.7   521.3 1990.37
   538.3 1992.75   550.9 1993.32   557.5 1992.67   559.5 1992.97   560.8 1993.24
   577.3 2001.24   589.6 2007.64   605.9 2011.77  615.232012.409   623.4 2012.75
#Mann= 5 ,-1 , 0
       0      .1       0   79.48     .05       0   432.3    .045       0
   456.9     .06       0  615.23      .1       0
#XS Ineff= 2 , 0
                          507.66         1991.68
Permanent Ineff=
       F       F
Bank Sta=432.3,456.9
XS Rating Curve= 0 ,0
Exp/Cntr(USF)=0,0
Exp/Cntr=0.3,0.1

Type RM Length L Ch R = 1 ,6320    ,59.8,59.8,59.8
XS GIS Cut Line= 2
2198205.53632092331000.985645388  2198932.664518331166.898862591
#Sta/Elev= 30
       0  2008.6    15.1 1998.34    25.2  1993.5      42 1991.83   61.021992.653
     106 1990.41   159.8 1992.43   244.4 1992.02     365 1989.19   445.8 1990.75
   455.9  1987.4   472.8 1985.14   476.1 1983.57   482.8 1983.34     493 1983.99
   496.5 1985.17   499.7 1988.16   503.1 1989.54   546.8 1989.43   563.6 1995.69
   584.2 1999.04   614.1 2011.01  630.052012.729  664.082012.857     678 2013.03
   681.4  2014.1   691.5 2023.41   698.2 2025.58   708.3  2031.3   745.8  2045.5
#Mann= 6 ,-1 , 0
       0      .1       0   61.02     .06       0   472.8    .045       0
   496.5     .06       0  630.05      .1       0  664.08      .1       0
#XS Ineff= 2 , 0
          443.23 1994.76  506.54         1995.24
Permanent Ineff=
       F       F
Bank Sta=472.8,496.5
XS Rating Curve= 0 ,0
Exp/Cntr(USF)=0,0
Exp/Cntr=0.5,0.3