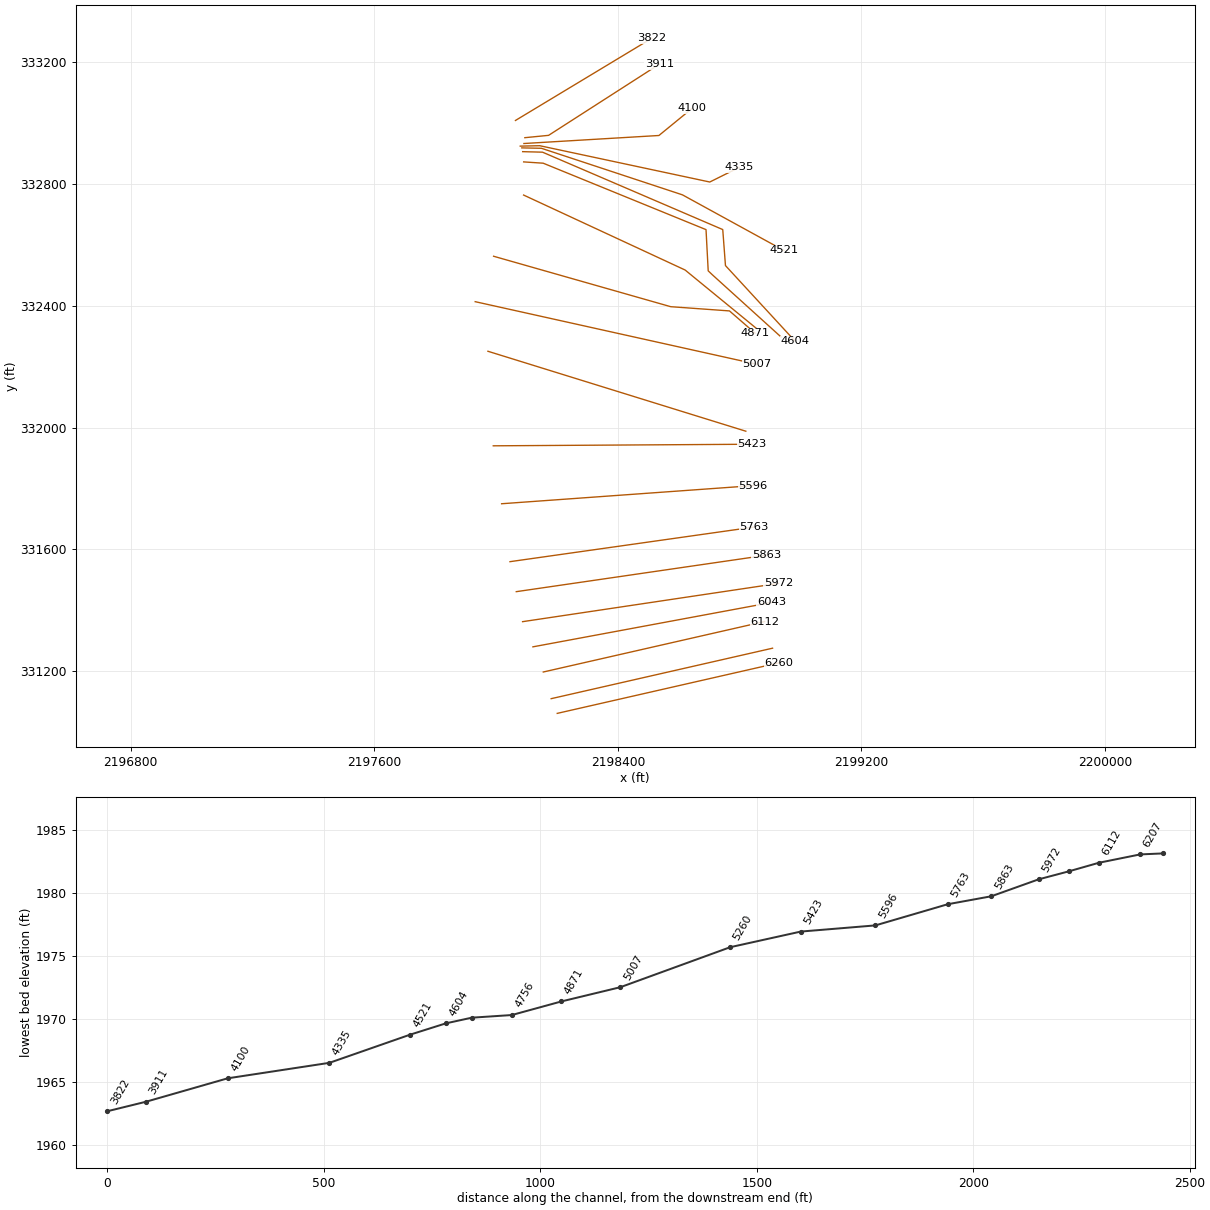
HEC-RAS study ANTNYCKT2.prj: ANTNYCKT2

--- ANTNYCKT2.g02 (geometry) --- (continued)

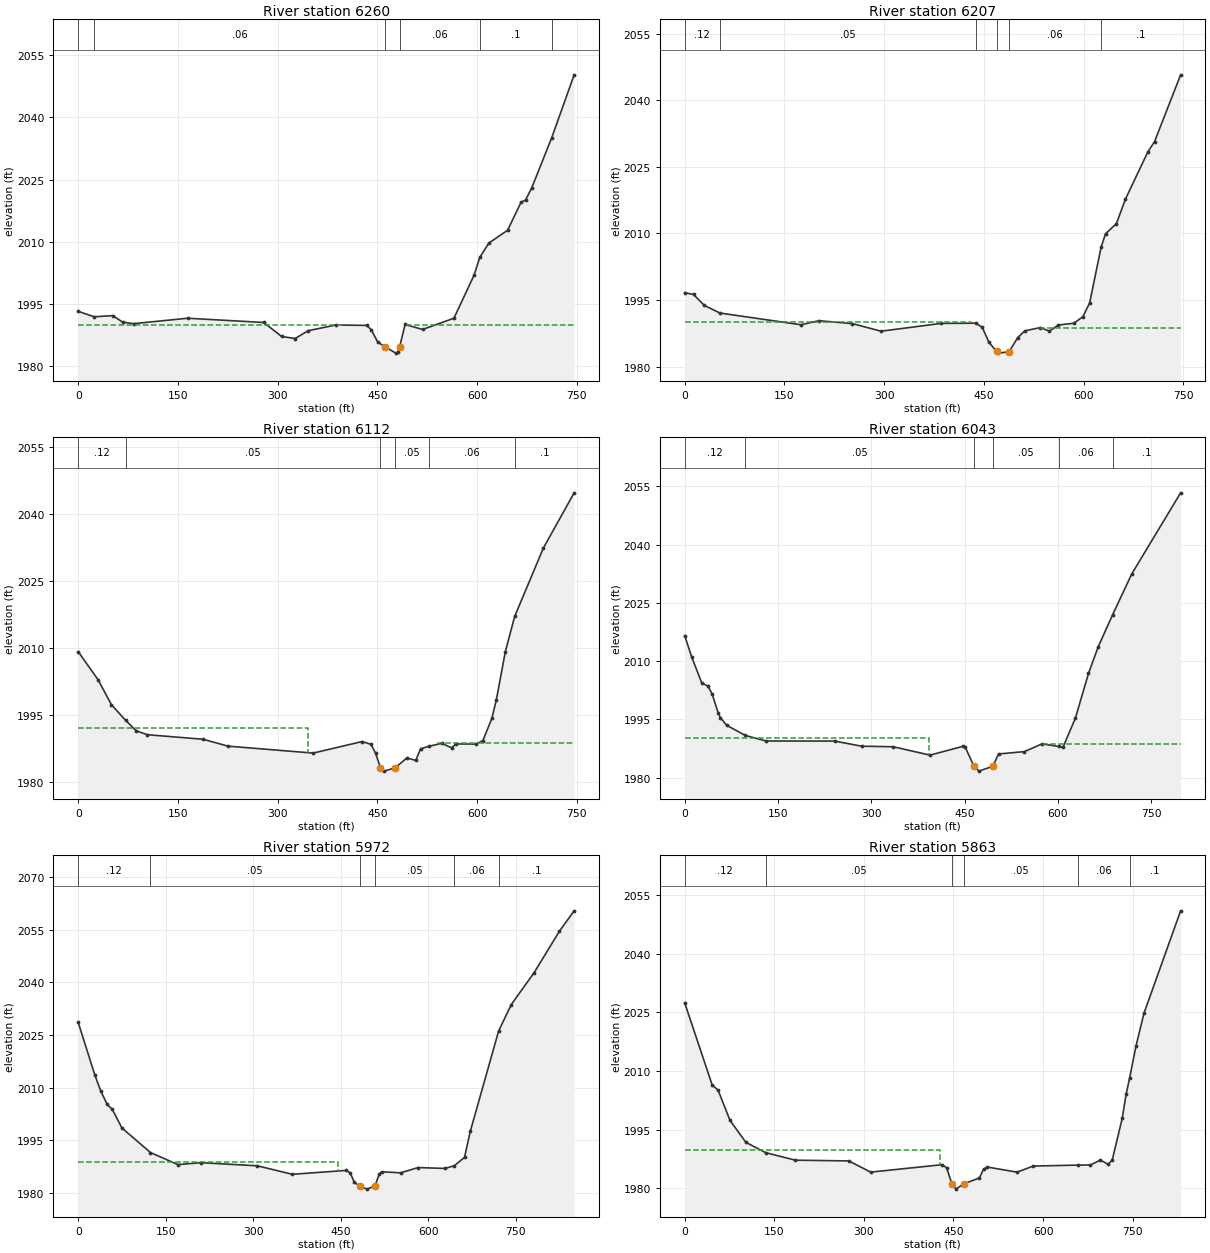
Type RM Length L Ch R = 1 ,6260    ,52.8,52.8,52.8
XS GIS Cut Line= 2
2198200.93402975331060.6496088252198928.06222684331226.562826028
#Sta/Elev= 30
       0  1993.2   24.121991.888      52 1992.17    66.9 1990.59    83.3 1990.23
   164.5 1991.54   278.9 1990.52   305.9 1987.14   326.1 1986.64     346 1988.54
   387.5 1989.91   433.7 1989.81   440.5 1988.81   450.5 1985.77   461.5 1984.66
   477.5 1983.12   480.9 1983.36   483.4 1984.68   491.6 1990.03   517.9 1988.83
     565 1991.54   595.3 2001.93  603.822006.208   617.6 2009.69   645.7 2012.77
   665.9 2019.52   672.7 2020.07   681.8 2022.92  712.142035.125   745.8 2050.28
#Mann= 6 ,-1 , 0
       0     .12       0   24.12     .06       0   461.5    .045       0
   483.4     .06       0  603.82      .1       0  712.14      .1       0
#XS Ineff= 2 , 0
          396.47 1990.02  492.87            1990
Permanent Ineff=
       F       F
Bank Sta=461.5,483.4
XS Rating Curve= 0 ,0
Exp/Cntr(USF)=0,0
Exp/Cntr=0.5,0.3

Type RM Length L Ch R = 1 ,6207    ,95,95,95
XS GIS Cut Line= 2
2198181.02144646331108.9680152692198908.14964354331274.881232472
#Sta/Elev= 30
       0 1996.66    13.3 1996.25    29.5 1993.79      531992.067   174.9 1989.43
   201.8 1990.34   252.3 1989.68   295.3 1987.98   385.7 1989.73   437.61989.782
   447.4 1988.87   457.5 1985.49     469 1983.43     471 1983.04   487.8 1983.33
   500.8 1986.53   511.4 1988.05   534.9  1988.8   548.4 1987.98   561.9 1989.37
   585.4 1989.77   598.9 1991.25     609 1994.35  626.262006.906   632.9 2009.92
   649.3 2012.21   662.8 2017.71   696.5 2028.34   706.6 2030.66   745.8  2045.7
#Mann= 6 ,-1 , 0
       0     .12       0      53     .05       0   437.6     .06       0
     469    .045       0   487.8     .06       0  626.26      .1       0
#XS Ineff= 2 , 0
           430.3 1990.01   532.1         1988.76
Permanent Ineff=
       F       F
Bank Sta=469,487.8
XS Rating Curve= 0 ,0
Exp/Cntr(USF)=0,0
Exp/Cntr=0.5,0.3

Type RM Length L Ch R = 1 ,6112    ,69.5,69.5,69.5
XS GIS Cut Line= 2
2198155.12518631331196.646680146 2198882.2533834331362.559897349
#Sta/Elev= 30
       0 2009.13    29.9 2002.84      50 1997.24   71.181993.781      87 1991.43
   103.8 1990.54     188 1989.51     225 1987.98   353.3 1986.42   426.9    1989
   440.3 1988.38   447.1 1986.43   454.51983.135   460.1 1982.38   476.6 1983.12
   494.2 1985.32   507.7 1984.79   514.9 1987.38  527.12 1987.93   546.8 1988.61
   561.5 1987.59   568.2 1988.47   598.5 1988.44   608.6 1989.23   622.1 1994.21
   628.8 1998.35   642.3 2009.12   656.42017.039   699.5 2032.33   745.8  2044.7
#Mann= 6 ,-1 , 0
       0     .12       0   71.18     .05       0   454.5    .045       0
   476.6     .05       0  527.12     .06       0   656.4      .1       0
#XS Ineff= 2 , 0
          345.81 1991.95  541.23         1988.57
Permanent Ineff=
       F       F
Bank Sta=454.5,476.6
XS Rating Curve= 0 ,0
Exp/Cntr(USF)=0,0
Exp/Cntr=0.3,0.1

Type RM Length L Ch R = 1 ,6043    ,70.2,70.2,70.2
XS GIS Cut Line= 2
2198121.11834679331279.3630921462198905.00537056331425.197666083
#Sta/Elev= 30
       0 2016.58    11.5 2010.99    27.4 2004.43    37.4 2003.57    44.1 2001.58
    54.1 1996.59    57.5 1995.44    67.5 1993.51    97.5 1990.89   130.9 1989.46
     241 1989.44   284.4 1988.12   335.1 1987.98   394.5 1985.82   447.9 1988.11
   451.2 1987.81   464.8 1983.04   472.9  1981.7   495.4 1982.95   504.6 1986.12
   546.1 1986.72   574.7 1988.73  601.071988.047   608.1 1987.81   628.1 1995.33
   649.2 2006.85   664.8 2013.69  687.872021.933   718.9 2032.51   797.3 2053.35
#Mann= 6 ,-1 , 0
       0     .12       0    97.5     .05       0   464.8    .045       0
   495.4     .05       0  601.07     .06       0  687.87      .1       0
#XS Ineff= 2 , 0
           393.3 1990.31  574.96         1988.73
Permanent Ineff=
       F       F
Bank Sta=464.8,495.4
XS Rating Curve= 0 ,0
Exp/Cntr=0.3,0.1

Type RM Length L Ch R = 1 ,5972    ,109,109,109
XS GIS Cut Line= 2
2198087.11150727331362.0795041462198927.75735773331487.835434817
#Sta/Elev= 30
       0  2028.6    28.5 2013.61    38.4 2009.12    49.7  2005.2    58.3 2003.84
    74.9 1998.51  123.811991.495   170.9 1988.06   210.9  1988.6   307.1 1987.71
   366.9 1985.29   459.7  1986.4   466.4 1985.68     473 1983.05     483 1981.82
   495.2 1981.06   508.6 1981.97   516.1 1985.43   520.1 1986.01   552.6 1985.71
   582.5 1987.21   628.9 1986.96  644.741987.763   662.1 1990.12     672 1997.55
  720.55 2026.16   742.3 2033.72   781.5 2042.83   824.6 2054.59     850 2060.44
#Mann= 6 ,-1 , 0
       0     .12       0  123.81     .05       0     483    .045       0
   508.6     .05       0  644.74     .06       0  720.55      .1       0
#XS Ineff= 2 , 0
          445.72 1988.72
Permanent Ineff=
       F       F
Bank Sta=483,508.6
XS Rating Curve= 0 ,0
Exp/Cntr(USF)=0,0
Exp/Cntr=0.3,0.1

Type RM Length L Ch R = 1 ,5863    ,100.5,100.5,100.5
XS GIS Cut Line= 2
 2198066.4308034331460.6864701982198887.98258161331580.487798586
#Sta/Elev= 30
       0 2027.48    46.1 2006.39      56 2005.06    75.9 1997.32   102.4 1991.72
  135.641989.068   185.3 1987.14   274.8 1986.95   311.3 1984.08   430.7 1985.98
   438.3 1985.25   447.5 1980.99   453.9 1979.72   467.1 1981.06   493.3 1982.58
   500.3 1984.83   506.9 1985.37   556.6 1984.07   583.4 1985.63   658.2 1985.88
   679.3 1985.91   695.9 1987.16   709.2 1986.06   715.8 1987.23   732.4 1997.83
     739 2004.06  744.762008.159   755.6 2016.45   768.8 2024.77   830.2 2051.05
#Mann= 6 ,-1 , 0
       0     .12       0  135.64     .05       0   447.5    .045       0
   467.1     .05       0   658.2     .06       0  744.76      .1       0
#XS Ineff= 2 , 0
          427.44 1989.74
Permanent Ineff=
       F       F
Bank Sta=447.5,467.1
XS Rating Curve= 0 ,0
Exp/Cntr=0.3,0.1

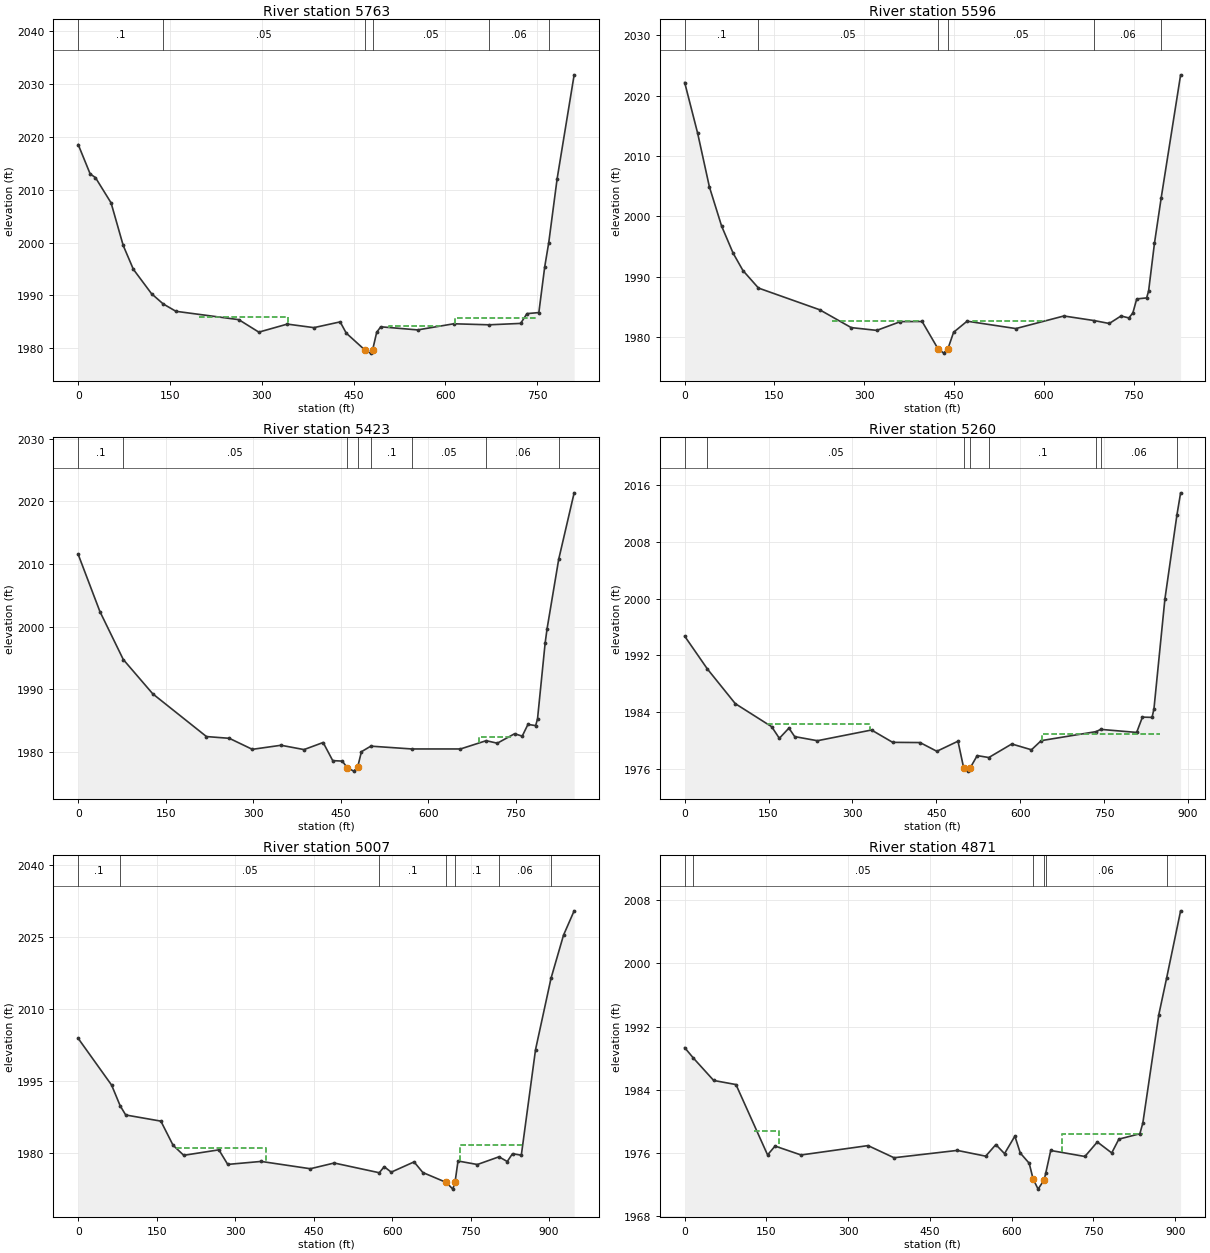
Type RM Length L Ch R = 1 ,5763    ,167.2,167.2,167.2
XS GIS Cut Line= 2
2198045.75009953 331559.293436252198848.20780549331673.140162355
#Sta/Elev= 30
       0 2018.53    19.5 2012.99    28.2 2012.28    53.7 2007.51    73.5 1999.46
    90.1 1994.95   119.9 1990.32  138.81  1988.4   159.7    1987   262.4 1985.42
   295.2 1983.06   341.7 1984.58   385.2 1983.91   428.1    1985     438 1982.88
     4691979.627   477.8 1979.09     481 1979.63   487.8 1983.03   494.4 1984.07
   554.7 1983.48   613.7 1984.64  671.661984.447     723 1984.71   733.4 1986.56
   752.8 1986.76   762.4 1995.41  768.931999.945   782.7 2012.08   810.5 2031.72
#Mann= 6 ,-1 , 0
       0      .1       0  138.81     .05       0     469    .045       0
     481     .05       0  671.66     .06       0  768.93      .1       0
#XS Ineff= 3 ,-1
  197.87  342.47 1985.85  508.33  594.82 1984.25  615.54  748.87  1985.8
Permanent Ineff=
       F       F       F
Bank Sta=469,481
XS Rating Curve= 0 ,0
Exp/Cntr(USF)=0,0
Exp/Cntr=0.3,0.1

Type RM Length L Ch R = 1 ,5596    ,172.3,172.3,172.3
XS GIS Cut Line= 2
2198018.26977555 331749.692491032198844.49070313331809.211336421
#Sta/Elev= 30
       0 2022.15    21.7 2013.75    41.3 2004.89    61.6 1998.44    80.8 1993.96
    97.3 1991.07  123.261988.168   225.5 1984.58   278.2 1981.63   320.9 1981.17
   360.4 1982.62   396.6 1982.64   422.9 1978.17   432.7 1977.41   439.8 1978.16
   449.2 1980.86   471.7 1982.69   553.2 1981.47   633.4 1983.55  683.891982.793
   709.2 1982.31   728.8 1983.55     742 1983.23   748.6 1984.05   755.1 1986.37
   771.6 1986.54   774.9 1987.66   784.7 1995.56  796.012003.115   828.4 2023.42
#Mann= 6 ,-1 , 0
       0      .1       0  123.26     .05       0   422.9    .045       0
   439.8     .05       0  683.89     .06       0  796.01      .1       0
#XS Ineff= 3 ,-1
  245.39  392.57 1982.72  480.87  604.13 1982.77  635.41   828.4  1983.5
Permanent Ineff=
       F       F       F
Bank Sta=422.9,439.8
XS Rating Curve= 0 ,0
Exp/Cntr=0.3,0.1

Type RM Length L Ch R = 1 ,5423    ,163.1,163.1,163.1
XS GIS Cut Line= 2
2197990.78945156 331940.091545812198840.77360076331945.282510488
#Sta/Elev= 30
       0 2011.52    37.2  2002.4   77.261994.739   127.8 1989.26   219.8 1982.44
     259 1982.16   298.4  1980.4   347.6 1981.05     387 1980.36   419.8 1981.49
   436.2  1978.6   452.6 1978.52   461.2 1977.46   472.3 1976.92   478.8 1977.51
   485.4 1980.02  501.511980.908  571.82 1980.46   655.2 1980.46  699.221981.779
   718.3 1981.38   747.9 1982.89     761 1982.51   770.8 1984.38     784 1984.19
   787.2 1985.24   800.3 1997.39   803.6 1999.66  823.512010.741     850 2021.36
#Mann= 8 ,-1 , 0
       0      .1       0   77.26     .05       0   461.2    .045       0
   478.8     .05       0  501.51      .1       0  571.82     .05       0
  699.22     .06       0  823.51      .1       0
#XS Ineff= 1 ,-1
  686.22  745.68 1982.44
Permanent Ineff=
       F
Bank Sta=461.2,478.8
XS Rating Curve= 0 ,0
Exp/Cntr(USF)=0,0
Exp/Cntr=0.3,0.1

Type RM Length L Ch R = 1 ,5260    ,253.4,253.4,253.4
XS GIS Cut Line= 2
2197973.30503376332250.8544577992198820.32097612331988.108238655
#Sta/Elev= 30
       0 1994.72   40.631990.087    90.5  1985.2   155.5 1981.95   169.3 1980.31
   186.4 1981.75   196.7 1980.55   237.3 1979.97   334.1 1981.48   371.9 1979.74
   420.9 1979.71   450.9 1978.48   488.7  1979.9     499 1976.09   505.9 1975.68
     510 1976.07   523.1 1977.87  543.811977.599   584.9 1979.51   620.1 1978.69
   637.5 1979.98  735.711981.254  743.951981.569   808.2 1981.14   818.5  1983.3
   835.7 1983.26   839.1 1984.45   858.7 1999.96  880.272011.854   886.8 2014.94
#Mann= 8 ,-1 , 0
       0      .1       0   40.63     .05       0     499    .045       0
     510     .05       0  543.81      .1       0  735.71     .05       0
  743.95     .06       0  880.27      .1       0
#XS Ineff= 2 ,-1
  147.43  331.02 1982.26  638.71   849.6  1980.9
Permanent Ineff=
       F       F
Bank Sta=499,510
XS Rating Curve= 0 ,0
Exp/Cntr=0.3,0.1

Type RM Length L Ch R = 1 ,5007    ,136.2,136.2,136.2
XS GIS Cut Line= 2
2197931.48380499332413.8379758352198856.90547552332208.094631213
#Sta/Elev= 30
       0 2003.85    63.9 1994.13   80.211989.835    90.8 1987.93     158 1986.65
   181.3 1981.64   201.7 1979.54   268.9 1980.68   285.8 1977.65   349.6 1978.27
   443.7 1976.75   489.3 1977.94   575.51975.918   584.9 1977.17   598.3 1976.04
     642 1978.17   658.8 1975.96   703.8 1973.89     716 1972.51   720.3 1973.95
     726 1978.36     763 1977.63  804.351979.231   820.1 1978.25   830.2 1979.88
     847 1979.56   874.2 2001.53  903.852016.379   927.7 2025.33     948 2030.38
#Mann= 7 ,-1 , 0
       0      .1       0   80.21     .05       0   575.5      .1       0
   703.8    .045       0   720.3      .1       0  804.35     .06       0
  903.85     .12       0
#XS Ineff= 2 ,-1
  189.15  358.83 1981.07  730.18  853.96 1981.69
Permanent Ineff=
       F       F
Bank Sta=703.8,720.3
XS Rating Curve= 0 ,0
Exp/Cntr(USF)=0,0
Exp/Cntr=0.3,0.1

Type RM Length L Ch R = 1 ,4871    ,114.7,114.7,114.7
XS GIS Cut Line= 4
2197991.93647224332563.1603321982198573.77391895332397.338920885
2198766.68728418332383.4707352152198850.82707975332310.379162057
#Sta/Elev= 30
       0 1989.32   16.061987.992    53.2 1985.16    94.1 1984.64   152.1 1975.72
   165.8 1976.84   213.5 1975.71   336.4  1976.9   384.1 1975.36   500.1 1976.29
   552.3 1975.56   570.9 1977.03   586.8 1975.88   605.8  1978.1   615.7 1975.96
   632.1 1974.66   639.2 1972.68   648.4 1971.38   659.4 1972.54  662.361973.373
   671.6 1976.28   734.3 1975.52   757.1 1977.36   783.5 1975.97   796.6 1977.72
   835.1  1978.4   840.6 1979.77   869.9 1993.51  884.331998.181   909.9 2006.67
#Mann= 6 ,-1 , 0
       0      .1       0   16.06     .05       0   639.2    .045       0
   659.4     .05       0  662.36     .06       0  884.33      .1       0
#XS Ineff= 2 ,-1
  127.96  172.46 1978.74  692.63  841.45 1978.38
Permanent Ineff=
       F       F
Bank Sta=639.2,659.4
XS Rating Curve= 0 ,0
Exp/Cntr=0.3,0.1

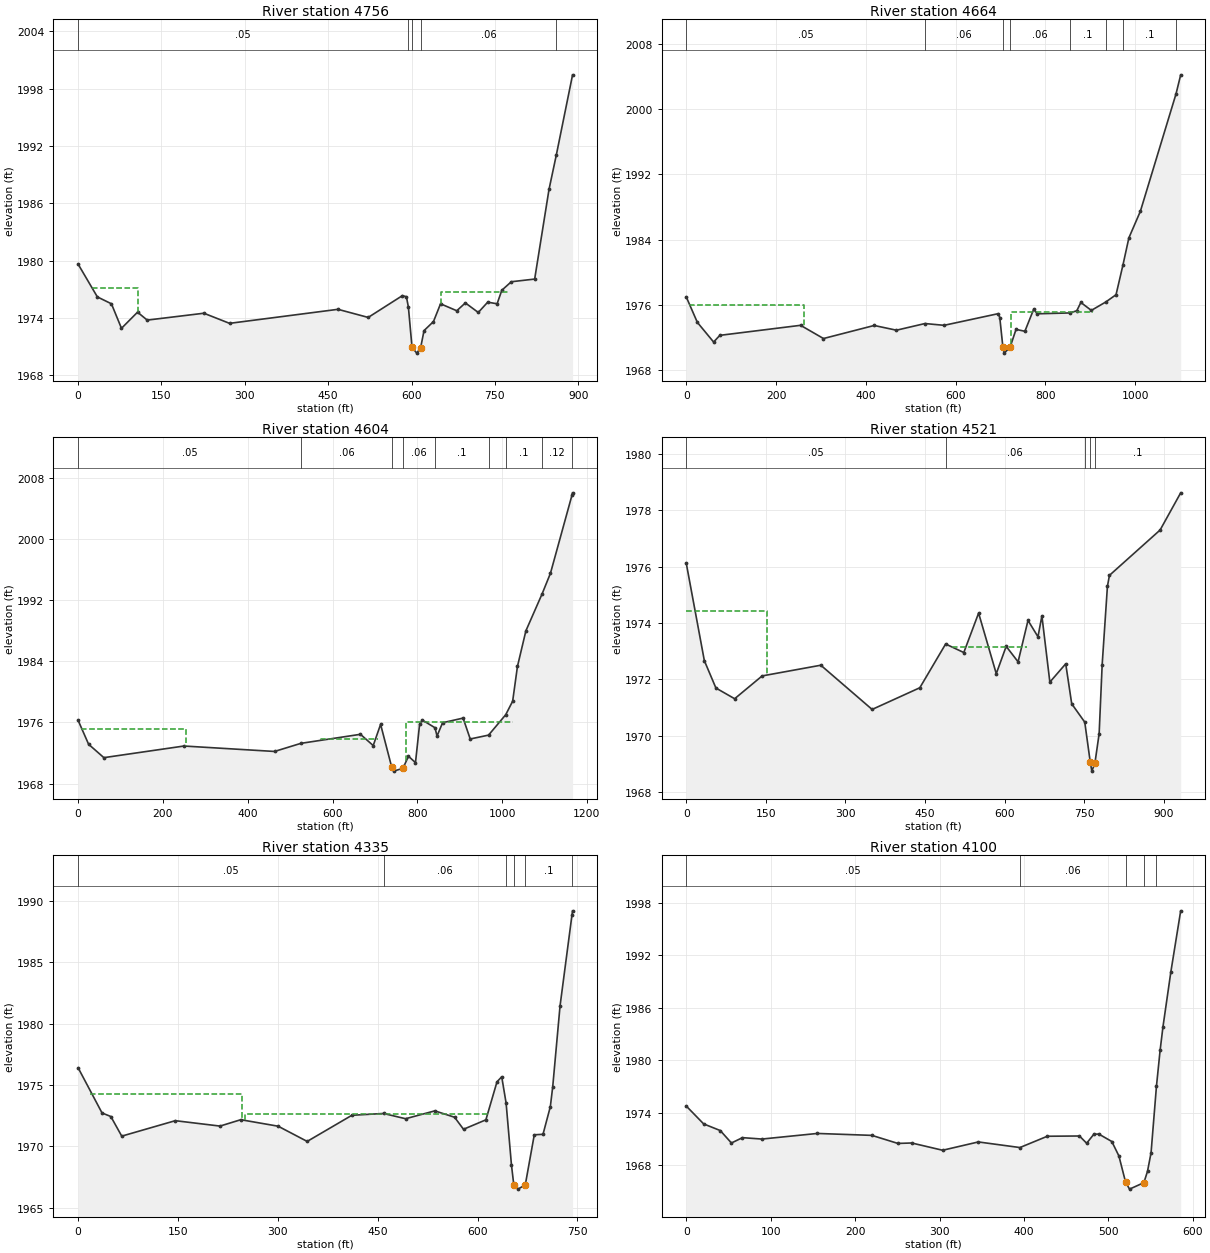
Type RM Length L Ch R = 1 ,4756    ,92.5,92.5,92.5
XS GIS Cut Line= 3
2198090.47358856332764.3091665052198620.93099619332517.910451818
2198856.76678751332324.659127734
#Sta/Elev= 30
       0 1979.62    34.6 1976.19    59.9 1975.47      78  1972.9   106.9 1974.59
   124.3 1973.76   226.3 1974.48   272.5 1973.42   467.6 1974.89     522 1974.04
   583.7 1976.33   590.8  1976.2  594.34 1975.13   600.91970.897   609.4  1970.3
   616.4 1970.88   622.5 1972.66   639.5 1973.61   652.2 1975.47   681.4 1974.74
   696.9 1975.56   720.1 1974.56   737.1 1975.64     754 1975.47   762.5 1976.89
   779.6 1977.78   821.6 1978.06   847.4 1987.45  860.56 1991.06   889.8 1999.46
#Mann= 5 ,-1 , 0
       0     .05       0  594.34     .06       0   600.9    .045       0
   616.4     .06       0  860.56      .1       0
#XS Ineff= 2 ,-1
   25.03  108.48 1977.09  652.29   773.3 1976.71
Permanent Ineff=
       F       F
Bank Sta=600.9,616.4
XS Rating Curve= 0 ,0
Exp/Cntr=0.5,0.3

Type RM Length L Ch R = 1 ,4664    ,63.7,59.8,60.1
XS GIS Cut Line= 6
2198090.63776491332873.273488197 2198154.8115679332869.017731178
  2198689.646171332650.6603405472198696.81375919332515.107155854
2198712.16672328332500.6717756282198936.20875839332297.678831382
#Sta/Elev= 30
       0 1976.98    24.7 1973.86    60.9 1971.45    74.8 1972.27   254.6  1973.5
   305.6 1971.88   418.5 1973.48   468.1  1972.9  531.511973.717   574.2  1973.5
   694.9 1974.93   698.2 1974.45   705.1 1970.85   708.1 1970.09   721.2 1970.82
   734.4    1973   754.1 1972.77   773.8 1975.48   781.3 1974.91  854.011975.018
   869.6 1975.28   878.8  1976.3   902.1 1975.33  934.371976.363   957.1 1977.25
   972.41980.867   985.7 1984.22  1011.3 1987.48 1090.78 2001.89  1101.1 2004.21
#Mann= 8 ,-1 , 0
       0     .05       0  531.51     .06       0   705.1    .045       0
   721.2     .06       0  854.01      .1       0  934.37     .06       0
   972.4      .1       0 1090.78     .12       0
#XS Ineff= 2 ,-1
    6.68  262.03 1976.03  723.59  906.86 1975.08
Permanent Ineff=
       F       F
Bank Sta=705.1,721.2
XS Rating Curve= 0 ,0
Exp/Cntr(USF)=0,0
Exp/Cntr=0.5,0.3

Type RM Length L Ch R = 1 ,4604    ,82.9,82.9,82.9
XS GIS Cut Line= 5
2198087.37897812332906.949944024 2198152.6829871332905.203604728
2198744.58617119332650.8458811222198753.47776256332532.524366215
2198982.35965715332283.857798369
#Sta/Elev= 30
       0 1976.27    24.7 1973.15    60.7  1971.4   249.6 1972.92   463.2 1972.21
  525.46 1973.27   665.9 1974.45     696 1972.98   713.4 1975.75   739.7 1970.14
   744.3 1969.64   766.1 1970.01   779.2 1971.58   795.7 1970.75   805.5 1975.81
   812.1  1976.3  841.741975.308   846.5 1974.22   859.6 1975.96     908 1976.57
   924.8 1973.84  968.061974.345 1008.541977.012  1024.9 1978.78  1036.2 1983.32
  1056.1 1987.97 1094.381992.801  1114.1  1995.5 1165.112005.754  1166.2    2006
#Mann= 9 ,-1 , 0
       0     .05       0  525.46     .06       0   739.7    .045       0
   766.1     .06       0  841.74      .1       0  968.06     .12       0
 1008.54      .1       0 1094.38     .12       0 1165.11      .1       0
#XS Ineff= 3 ,-1
   10.01  253.69 1975.15  572.07  707.251973.807  774.21 1025.22    1976
Permanent Ineff=
       F       F       F
Bank Sta=739.7,766.1
XS Rating Curve= 0 ,0
Exp/Cntr(USF)=0,0
Exp/Cntr=0.5,0.3

Type RM Length L Ch R = 1 ,4521    ,186,186,186
XS GIS Cut Line= 4
2198084.51568623332919.3676690512198149.13535244 332917.97508951
2198612.20630018332764.9914115492198945.01614893332582.388238254
#Sta/Elev= 30
       0 1976.12    34.1 1972.66    55.9 1971.69    91.2 1971.31     143 1972.12
   253.6  1972.5   350.3 1970.93   440.2  1971.7  488.851973.253   523.1 1972.95
     551 1974.35   584.3  1972.2     603 1973.17   625.4 1972.62   644.1 1974.09
   662.9 1973.51   670.3 1974.25   685.3  1971.9   715.2 1972.55   726.5 1971.13
  751.071970.479   761.3 1969.08   764.4 1968.74   770.2 1969.02   778.2 1970.07
   783.9 1972.52   793.8  1975.3   797.6 1975.69   893.1  1977.3   931.9 1978.62
#Mann= 5 ,-1 , 0
       0     .05       0  488.85     .06       0  751.07      .1       0
   761.3    .045       0   770.2      .1       0
#XS Ineff= 2 ,-1
  -92.07  151.321974.437   500.7  642.56 1973.16
Permanent Ineff=
       F       F
Bank Sta=761.3,770.2
XS Rating Curve= 0 ,0
Exp/Cntr(USF)=0,0
Exp/Cntr=0.3,0.1

Type RM Length L Ch R = 1 ,4335    ,235.1,235.1,235.1
XS GIS Cut Line= 4
2198079.34330952332925.1098096592198143.45913698332926.489412699
2198701.97504401332807.1521997712198798.10869817332854.936571422
#Sta/Elev= 30
       0  1976.4    35.9 1972.72    49.1 1972.43    65.5 1970.83   145.9 1972.09
   213.1 1971.65   244.3 1972.17   300.4 1971.64     344  1970.4   411.1 1972.53
  458.681972.678   491.8 1972.25   535.7 1972.89   565.4 1972.37   578.8 1971.39
   612.4 1972.16   629.1 1975.26   636.2 1975.67  642.781973.528   650.8 1968.49
   654.31966.869   660.6 1966.51   671.6 1966.86   685.1 1970.94   698.2 1970.98
   709.2 1973.23   712.8 1974.86   723.8 1981.45  741.76 1988.88   742.6  1989.2
#Mann= 6 ,-1 , 0
       0     .05       0  458.68     .06       0  642.78      .1       0
   654.3    .045       0   671.6      .1       0  741.76      .1       0
#XS Ineff= 2 ,-1
    17.8   245.9 1974.24  250.35  617.52 1972.64
Permanent Ineff=
       F       F
Bank Sta=654.3,671.6
XS Rating Curve= 0 ,0
Exp/Cntr(USF)=0,0
Exp/Cntr=0.3,0.1

Type RM Length L Ch R = 1 ,4100    ,188.9,188.9,188.9
XS GIS Cut Line= 3
2198091.44672588332933.6932833882198534.91579284332960.074039452
2198644.37161585333049.603715059
#Sta/Elev= 30
       0 1974.77    20.6 1972.73    40.3 1971.97    53.5 1970.55    66.6 1971.16
    89.6    1971   155.3 1971.64   219.9 1971.42   250.7  1970.5   267.1 1970.55
   303.7 1969.72     346 1970.67  395.24 1970.03   427.7 1971.32   465.8 1971.35
   474.3 1970.52   482.8 1971.55   488.7 1971.57   504.1 1970.72   512.5 1969.07
   520.4 1966.08   525.1 1965.28   542.1 1966.02   546.4 1967.32   550.6 1969.44
     5571977.049   561.3 1981.12   564.7 1983.82   574.1 1990.13   585.7 1997.07
#Mann= 5 ,-1 , 0
       0     .05       0  395.24     .06       0   520.4    .045       0
   542.1     .06       0     557      .1       0
#XS Ineff= 2 , 0
          488.18 1971.03
Permanent Ineff=
       F       F
Bank Sta=520.4,542.1
XS Rating Curve= 0 ,0
Exp/Cntr(USF)=0,0
Exp/Cntr=0.3,0.1

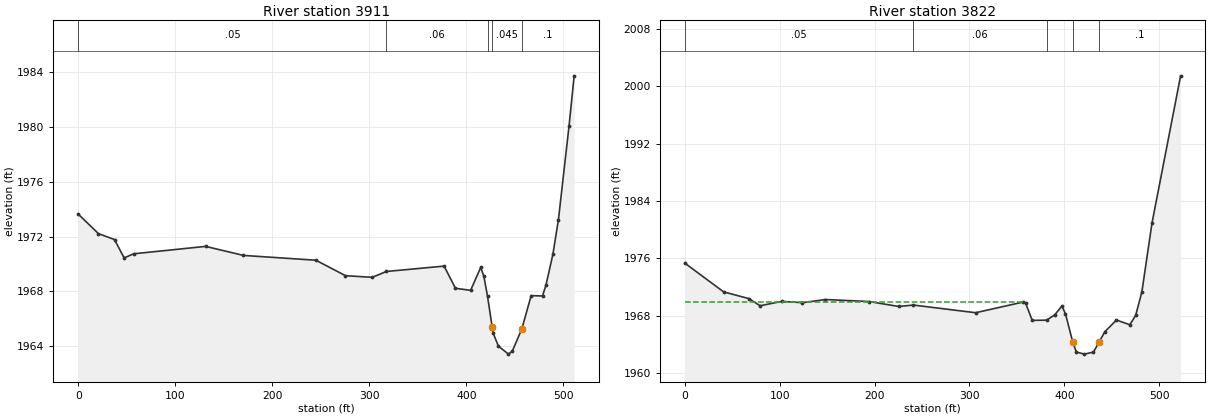
Type RM Length L Ch R = 1 ,3911    ,88.9,88.9,88.9
XS GIS Cut Line= 3
2198094.49480996332952.8522721792198172.54974121332960.546705452
2198536.37527631333194.484805834
#Sta/Elev= 30
       0 1973.65    20.9 1972.22    37.4 1971.79    47.3 1970.45    57.2 1970.75
   131.3 1971.29   170.3 1970.63   244.9 1970.28   275.4 1969.15   302.9 1969.03
   317.61969.458     377 1969.85   388.7 1968.23   404.3 1968.08   414.7 1969.75
   417.9 1969.12  421.721967.658   426.51965.423   427.7 1964.93   432.9 1964.01
   443.3 1963.42   447.2 1963.63     4571965.242   466.7 1967.69   478.4 1967.67
     482 1968.47   489.1 1970.71   494.8 1973.24   505.7 1980.06     511 1983.75
#Mann= 5 ,-1 , 0
       0     .05       0   317.6     .06       0  421.72      .1       0
   426.5    .045       0     457      .1       0
Bank Sta=426.5,457
XS Rating Curve= 0 ,0
Exp/Cntr(USF)=0,0
Exp/Cntr=0.3,0.1

Type RM Length L Ch R = 1 ,3822    ,88.9,88.9,88.9
XS GIS Cut Line= 2
2198063.72746636333009.4718022352198511.14104117333279.411495078
#Sta/Elev= 30
       0 1975.37    41.1 1971.34    67.9  1970.4    79.4 1969.41   102.4 1970.02
     124 1969.84   148.3 1970.28   194.1    1970   225.6 1969.31  240.941969.507
   306.5 1968.44   356.7 1969.93   359.1  1969.8   366.2 1967.37  381.251967.403
   389.7 1968.12   397.4 1969.36   401.2 1968.29   408.9 1964.31   412.7 1962.96
   421.2 1962.67   430.7 1962.96   436.5 1964.32   442.7  1965.8   454.9 1967.42
     469 1966.76   475.2 1968.08   481.7 1971.36   492.3  1980.9   522.5 2001.45
#Mann= 5 ,-1 , 0
       0     .05       0  240.94     .06       0  381.25      .1       0
   408.9    .045       0   436.5      .1       0
#XS Ineff= 2 , 0
          356.13 1969.92
Permanent Ineff=
       F       F
Bank Sta=408.9,436.5
XS Rating Curve= 0 ,0
Exp/Cntr(USF)=0,0
Exp/Cntr=0.3,0.1