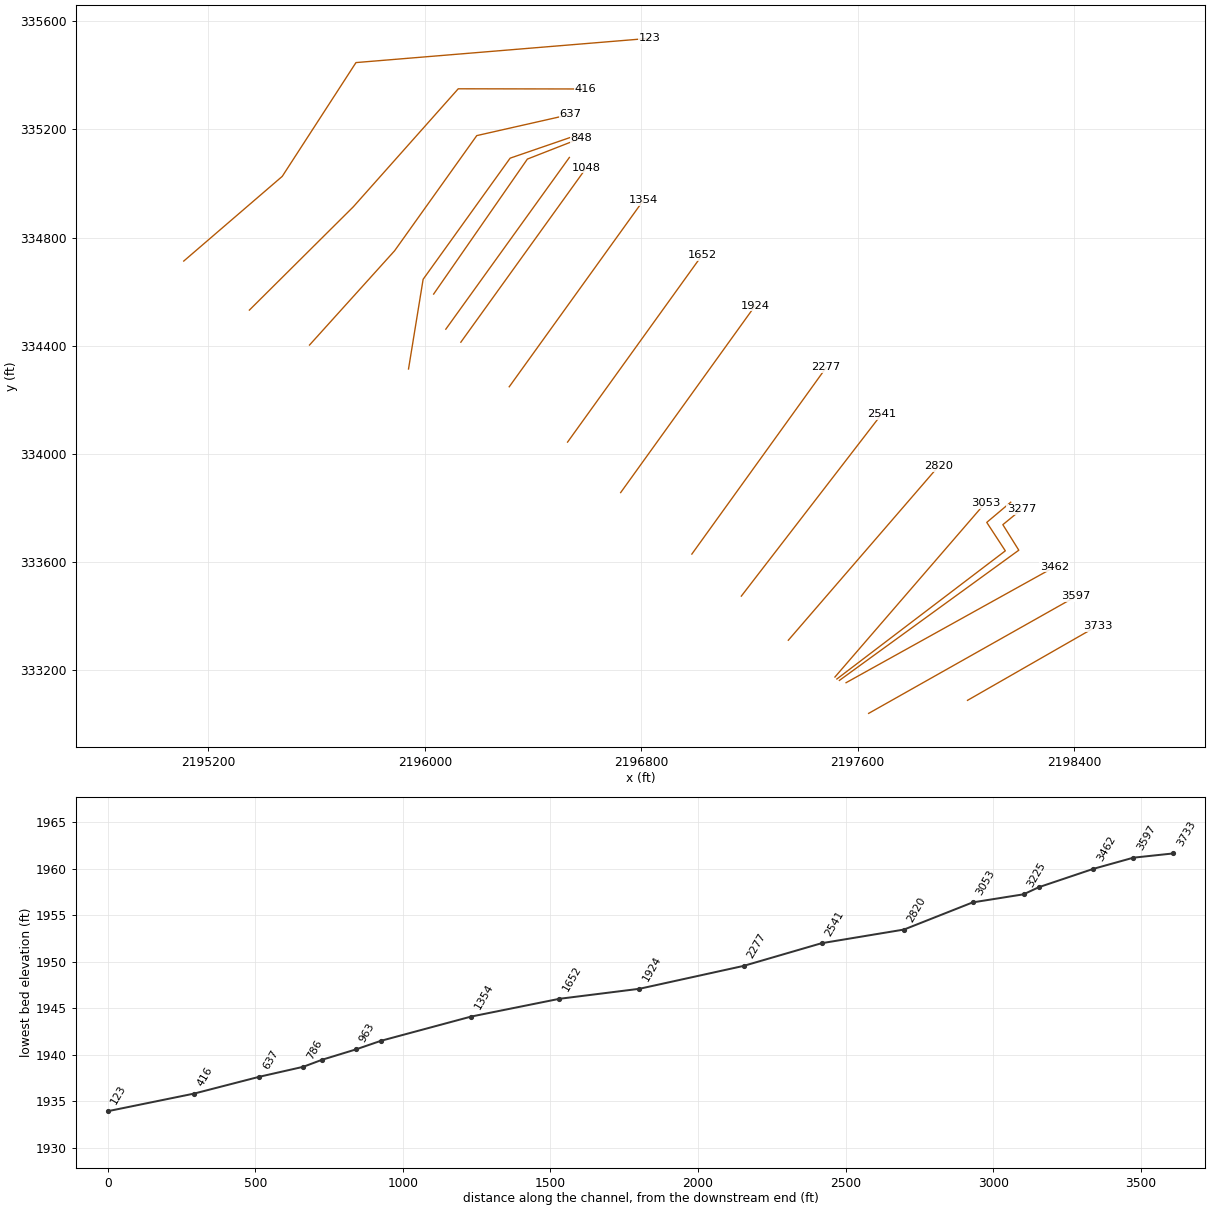
HEC-RAS study ANTNYCKT2.prj: ANTNYCKT2

--- ANTNYCKT2.g02 (geometry) --- (continued)

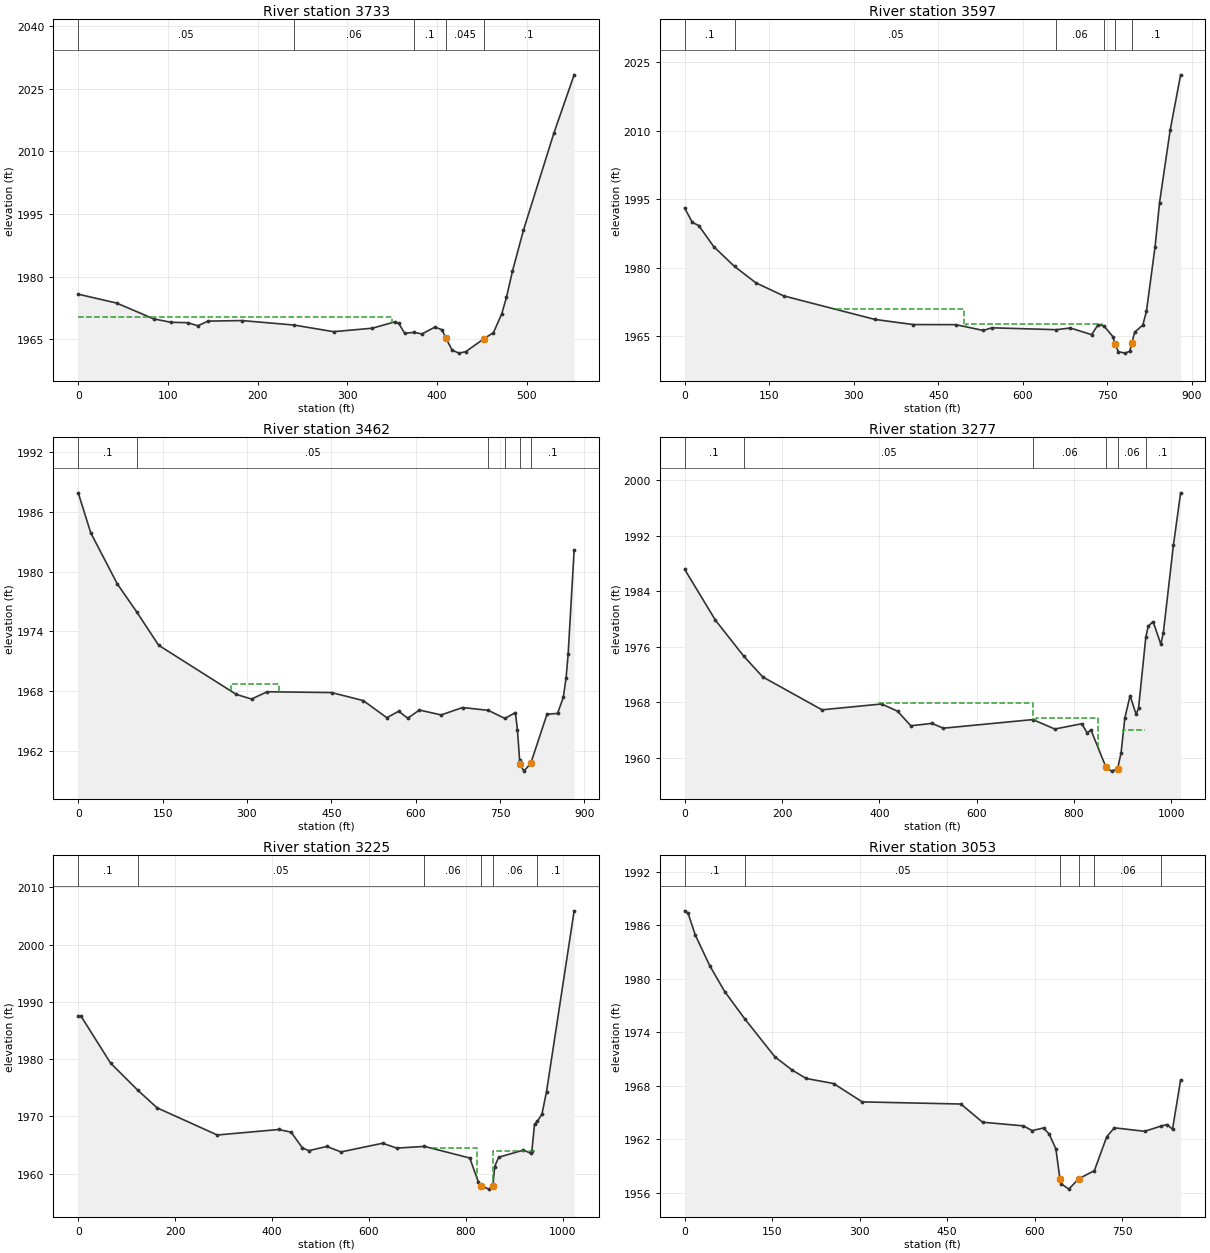
Type RM Length L Ch R = 1 ,3733    ,135.8,135.8,135.8
XS GIS Cut Line= 2
2198006.08568763333089.4228816162198485.90680602333364.338184323
#Sta/Elev= 30
       0 1975.79    42.7 1973.67    84.3 1969.87   103.2 1969.06   122.1 1968.96
   133.4 1968.22   144.8 1969.34   182.6 1969.47  240.441968.401   284.7 1966.81
     328 1967.64   352.7 1969.14   357.4  1968.8     364 1966.44  374.661966.631
   383.3 1966.26   397.7 1967.91   405.7 1967.26   410.11965.218     417 1962.36
   424.6 1961.67   432.1 1962.02   452.7 1965.16     463 1966.57   472.2 1971.05
   477.5 1975.01   484.2 1981.29   496.4 1991.06   530.4 2014.37     553 2028.33
#Mann= 5 ,-1 , 0
       0     .05       0  240.44     .06       0  374.66      .1       0
   410.1    .045       0   452.7      .1       0
#XS Ineff= 2 , 0
          350.15 1970.32
Permanent Ineff=
       F       F
Bank Sta=410.1,452.7
XS Rating Curve= 0 ,0
Exp/Cntr(USF)=0,0
Exp/Cntr=0.3,0.1

Type RM Length L Ch R = 1 ,3597    ,135.4,135.4,135.4
XS GIS Cut Line= 2
2197640.70898476333041.2545361812198407.00050023333473.461333931
#Sta/Elev= 30
       0 1993.05    13.7 1989.88      25 1989.21    51.7 1984.56   88.491980.236
   126.4 1976.63   175.7 1973.77   337.7  1968.6   405.5 1967.48   480.8 1967.46
   529.8 1966.19   544.9 1966.77  659.281966.355   684.2 1966.73   721.9 1965.26
   733.5 1967.47  743.55 1967.21   759.6 1964.83   763.3 1963.23   769.4 1961.53
   781.5 1961.21   789.7 1961.64   793.2 1963.44   798.3 1965.81   812.8 1967.38
   819.2 1970.42   834.5 1984.58   842.4 1994.23   861.3 2010.18   879.8 2022.29
#Mann= 6 ,-1 , 0
       0      .1       0   88.49     .05       0  659.28     .06       0
  743.55      .1       0   763.3    .045       0   793.2      .1       0
#XS Ineff= 2 ,-1
  267.66  495.17 1970.88  499.88  740.55 1967.51
Permanent Ineff=
       F       F
Bank Sta=763.3,793.2
XS Rating Curve= 0 ,0
Exp/Cntr=0.3,0.1

Type RM Length L Ch R = 1 ,3462    ,184.4,184.4,184.4
XS GIS Cut Line= 2
2197557.19997387333154.5833381072198328.09419444333582.584483539
#Sta/Elev= 30
       0 1987.89    22.3 1983.88    69.6 1978.76  103.921975.968     143 1972.62
   280.9  1967.7   308.1 1967.23   335.9 1967.96   450.7 1967.88     507 1967.07
   548.7 1965.36   569.7 1966.01   585.8 1965.31   606.6 1966.13   645.2 1965.64
   683.4 1966.38  728.851966.101  758.711965.283   777.2 1965.88   780.9 1964.14
   784.7 1961.14     786 1960.71   792.2 1960.01   804.5 1960.78   833.4 1965.71
   852.2 1965.79   862.4  1967.4   867.4 1969.37     871 1971.73   881.7 1982.18
#Mann= 6 ,-1 , 0
       0      .1       0  103.92     .05       0  728.85     .06       0
  758.71      .1       0     786    .045       0   804.5      .1       0
#XS Ineff= 1 ,-1
  272.45  356.16 1968.75
Permanent Ineff=
       F
Bank Sta=786,804.5
XS Rating Curve= 0 ,0
Exp/Cntr(USF)=0,0
Exp/Cntr=0.5,0.3

Type RM Length L Ch R = 1 ,3277    ,52.3,52.3,52.3
XS GIS Cut Line= 4
2197532.62747938333163.1464533222198195.64600003333644.392999937
2198136.70458365333738.7495480412198205.17219779333794.825583726
#Sta/Elev= 30
       0 1987.12    63.2  1979.8  121.511974.604   160.4 1971.62   282.1 1966.88
   404.7 1967.72   437.6 1966.67   464.6 1964.58     508 1964.92   531.5 1964.23
   715.41965.472   760.5 1964.11   815.8 1964.87     827 1963.55   834.7 1963.98
   865.7 1958.59   877.3 1958.04   889.5  1958.4   896.6 1960.65   904.4  1965.7
   915.2 1968.92   927.5 1966.23   932.5 1967.09  947.531977.373   952.5 1978.95
   962.5 1979.59   978.4 1976.33   983.5 1977.99  1004.2 1990.61    1019 1998.16
#Mann= 6 ,-1 , 0
       0      .1       0  121.51     .05       0   715.4     .06       0
   865.7    .045       0   889.5     .06       0  947.53      .1       0
#XS Ineff= 3 ,-1
  398.39  715.51 1967.82  721.99  849.27 1965.66  901.04  946.35 1964.02
Permanent Ineff=
       F       F       F
Bank Sta=865.7,889.5
XS Rating Curve= 0 ,0
Exp/Cntr(USF)=0,0
Exp/Cntr=0.5,0.3

Type RM Length L Ch R = 1 ,3225    ,172.3,172.3,172.3
XS GIS Cut Line= 4
 2197523.2180247333168.3210263122198145.83180381333642.011657922
2198077.23759305333747.1324270772198165.85731194333821.791411809
#Sta/Elev= 30
       0 1987.54       6 1987.47    66.9 1979.28  123.131974.543   162.9 1971.47
     287 1966.73   414.1 1967.69   439.5 1967.22   462.5  1964.5     476 1963.99
   513.1 1964.73   542.4 1963.77   628.5 1965.29   657.4 1964.44  714.741964.736
   808.2 1962.71   826.2 1958.45   832.31957.833   847.8 1957.27   855.9 1957.86
   859.6  1961.2   867.8 1962.84     919 1964.09   934.1 1963.54   936.4 1963.92
   941.9 1968.61  947.921969.142   957.2 1970.36   966.7 1974.32  1023.7  2005.9
#Mann= 6 ,-1 , 0
       0      .1       0  123.13     .05       0  714.74     .06       0
   832.3    .045       0   855.9     .06       0  947.92      .1       0
#XS Ineff= 2 ,-1
  730.23  822.62 1964.42  856.96  943.07 1964.01
Permanent Ineff=
       F       F
Bank Sta=832.3,855.9
XS Rating Curve= 0 ,0
Exp/Cntr(USF)=0,0
Exp/Cntr=0.5,0.3

Type RM Length L Ch R = 1 ,3053    ,232.6,232.6,232.6
XS GIS Cut Line= 2
2197516.11777866 333175.632265132198071.66662936333818.956036243
#Sta/Elev= 30
       0 1987.63     5.8 1987.37    18.2 1984.91      43 1981.47    68.6 1978.57
  103.021975.506   154.7 1971.24   183.8 1969.78   208.2 1968.82   255.2 1968.25
   304.3 1966.19   473.4 1965.95   510.6 1963.91   580.4  1963.5   595.5 1962.97
     615 1963.26   624.6 1962.59   636.2 1960.92   643.2 1957.53   645.4    1957
   658.4  1956.4   675.2 1957.56  702.151958.472   723.4 1962.28   736.4 1963.28
   788.4 1962.89  817.091963.486   826.9 1963.65   836.1 1963.12     850 1968.65
#Mann= 6 ,-1 , 0
       0      .1       0  103.02     .05       0   643.2    .045       0
   675.2     .05       0  702.15     .06       0  817.09      .1       0
Bank Sta=643.2,675.2
XS Rating Curve= 0 ,0
Exp/Cntr(USF)=0,0
Exp/Cntr=0.3,0.1

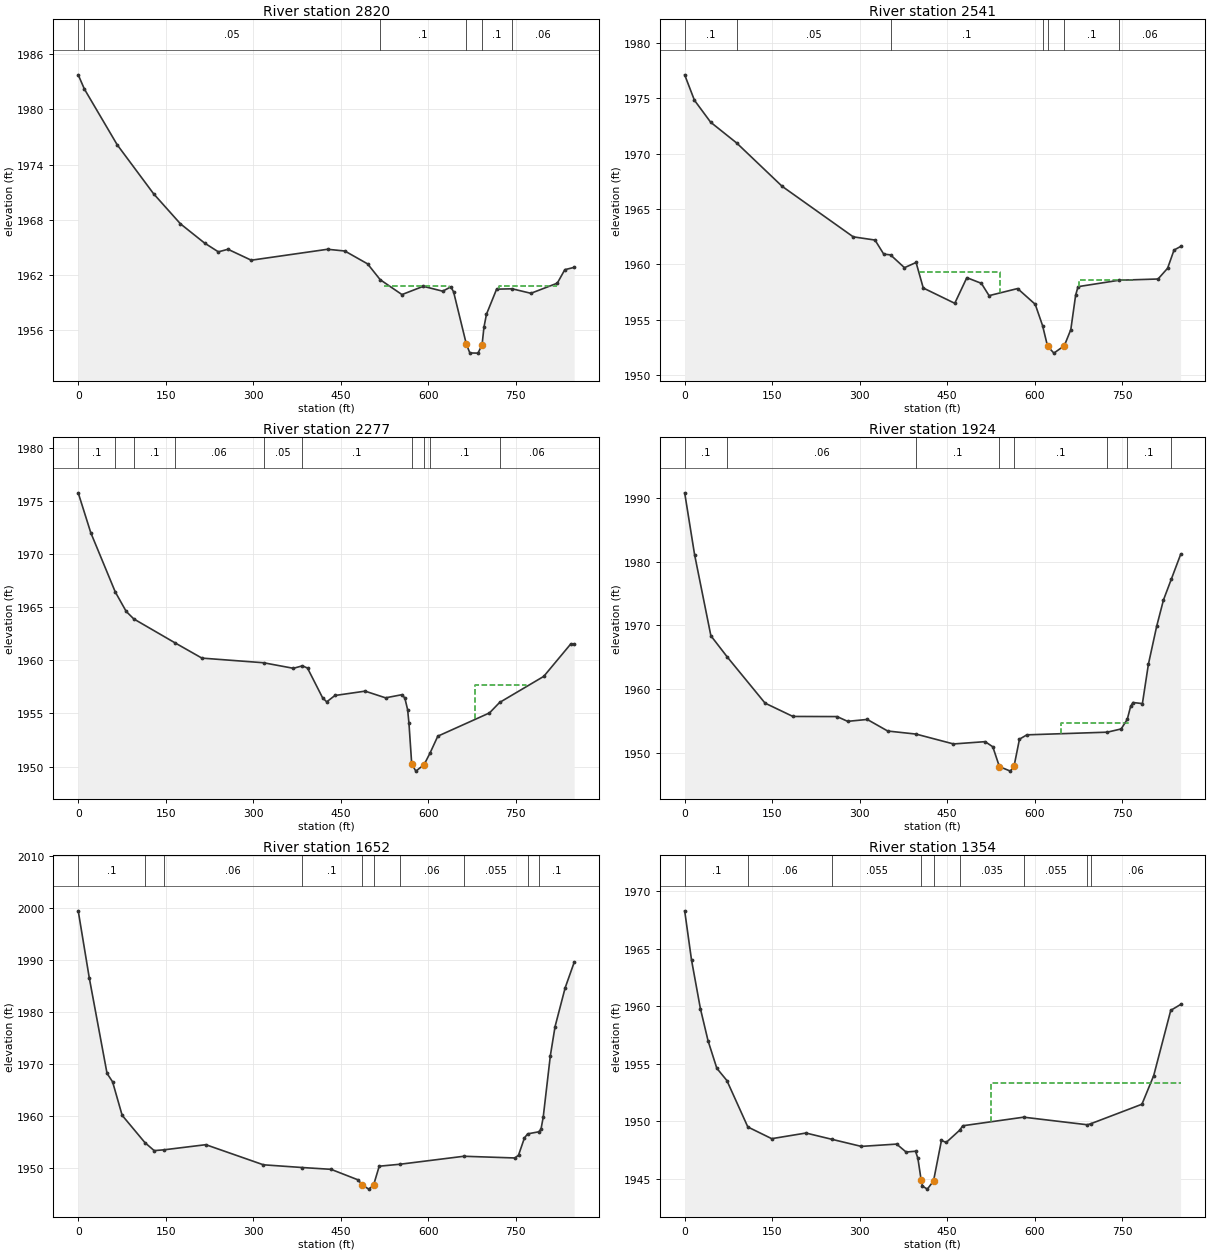
Type RM Length L Ch R = 1 ,2820    ,279.3,279.3,279.3
XS GIS Cut Line= 2
2197343.82628953333311.6518618072197899.37514023 333954.97563292
#Sta/Elev= 30
       0 1983.76   10.621982.209    66.8 1976.15   129.2 1970.82   175.2 1967.55
   216.5 1965.46   240.2  1964.5   256.7 1964.78   296.6 1963.59   427.4 1964.78
     457 1964.59     496 1963.19  517.58 1961.47   554.9 1959.85   591.4 1960.75
   624.7 1960.22   638.7 1960.69   643.4 1960.14   665.1 1954.49   671.2  1953.5
   685.2 1953.48   692.2 1954.39   695.4 1956.29   699.7 1957.71   717.1 1960.44
  743.721960.479   775.9 1959.99   821.1 1961.09     834 1962.56     850 1962.81
#Mann= 6 ,-1 , 0
       0      .1       0   10.62     .05       0  517.58      .1       0
   665.1    .045       0   692.2      .1       0  743.72     .06       0
#XS Ineff= 2 ,-1
  524.02  635.14  1960.8  720.72  819.82 1960.74
Permanent Ineff=
       F       F
Bank Sta=665.1,692.2
XS Rating Curve= 0 ,0
Exp/Cntr(USF)=0,0
Exp/Cntr=0.3,0.1

Type RM Length L Ch R = 1 ,2541    ,264.1,264.1,264.1
XS GIS Cut Line= 2
2197170.06951057333474.6404400322197689.08268828334147.786279629
#Sta/Elev= 30
       0 1977.09    16.7  1974.8    44.5 1972.82   89.081970.949   167.1 1967.04
   288.9 1962.49   326.2  1962.2   341.2 1960.93  352.811960.865   376.7 1959.71
   396.6 1960.18   408.9 1957.88   462.9  1956.5   483.6 1958.81   508.5  1958.3
   521.7 1957.19   570.6 1957.83   600.8 1956.41  613.441954.482   621.9 1952.64
   632.8 1952.01   650.7 1952.68   661.8 1954.13   670.1 1957.24   674.2    1958
  744.78 1958.58   811.3 1958.69   827.7 1959.66   838.7  1961.3     850 1961.62
#Mann= 7 ,-1 , 0
       0      .1       0   89.08     .05       0  352.81      .1       0
  613.44      .1       0   621.9    .045       0   650.7      .1       0
  744.78     .06       0
#XS Ineff= 2 ,-1
   400.9  540.54 1959.31  675.68  768.77 1958.56
Permanent Ineff=
       F       F
Bank Sta=621.9,650.7
XS Rating Curve= 0 ,0
Exp/Cntr(USF)=0,0
Exp/Cntr=0.3,0.1

Type RM Length L Ch R = 1 ,2277    ,352.8,352.8,352.8
XS GIS Cut Line= 2
2196987.24197985333630.0681264132197483.91211452334319.864311763
#Sta/Elev= 30
       0 1975.77    21.5 1972.02   63.521966.438    82.3  1964.6   95.341963.896
  165.581961.657     212 1960.21  317.641959.773   368.8 1959.25  384.291959.484
     393 1959.27   418.8 1956.48   425.9 1956.09     440 1956.69   491.7  1957.1
   526.8 1956.47   555.3 1956.77   559.9 1956.43   564.6 1955.35   566.9 1954.06
   571.6 1950.24   578.7 1949.57   592.8 1950.18  602.99 1951.27   616.3 1952.86
   704.9 1955.05  722.211956.033   797.9 1958.49   844.3 1961.55     850 1961.55
#Mann= 10 ,-1 , 0
       0      .1       0   63.52     .06       0   95.34      .1       0
  165.58     .06       0  317.64     .05       0  384.29      .1       0
   571.6    .045       0   592.8      .1       0  602.99      .1       0
  722.21     .06       0
#XS Ineff= 1 ,-1
  680.18  767.27 1957.64
Permanent Ineff=
       F
Bank Sta=571.6,592.8
XS Rating Curve= 0 ,0
Exp/Cntr(USF)=0,0
Exp/Cntr=0.3,0.1

Type RM Length L Ch R = 1 ,1924    ,271.4,271.4,271.4
XS GIS Cut Line= 2
2196724.14133875333857.3363174792197220.59643954334547.287281606
#Sta/Elev= 30
       0 1990.83      17 1981.11    44.9 1968.38   73.021965.037   137.8 1957.79
   185.5  1955.7   261.2 1955.68   279.3 1954.93   312.9 1955.23     348 1953.41
  396.51 1952.93   460.7 1951.38     515 1951.74   528.1 1950.93   539.4 1947.82
   558.2 1947.11   564.4 1947.84   573.8 1952.13   586.5 1952.81  724.51 1953.23
   748.1 1953.74  758.511955.237   764.3 1957.27   768.3 1957.89   784.5 1957.72
   794.8 1963.91     809 1969.88   820.6    1974  833.841977.217     850 1981.15
#Mann= 8 ,-1 , 0
       0      .1       0   73.02     .06       0  396.51      .1       0
   539.4    .045       0   564.4      .1       0  724.51     .06       0
  758.51      .1       0  833.84      .1       0
#XS Ineff= 1 ,-1
  645.65  762.76 1954.62
Permanent Ineff=
       F
Bank Sta=539.4,564.4
XS Rating Curve= 0 ,0
Exp/Cntr(USF)=0,0
Exp/Cntr=0.3,0.1

Type RM Length L Ch R = 1 ,1652    ,298.8,298.8,298.8
XS GIS Cut Line= 2
2196527.88629959334043.9517668322197024.34140038334733.902730959
#Sta/Elev= 30
       0 1999.45    18.9 1986.62    49.4 1968.25    58.9 1966.63    75.3  1960.2
  114.291954.964   130.2 1953.42  147.061953.576   218.7 1954.56   317.4  1950.7
  384.051950.176   433.3 1949.83   479.6 1947.81   486.7 1946.84     498 1946.03
   506.1 1946.76   515.9 1950.43  551.621950.808  660.961952.339   748.6 1952.01
   754.7 1952.56   764.8 1955.86  770.291956.634  789.01 1957.03   793.1 1957.48
     797 1959.86   809.2 1971.65   817.3 1977.24   834.6 1984.68     850 1989.55
#Mann= 10 ,-1 , 0
       0      .1       0  114.29    .055       0  147.06     .06       0
  384.05      .1       0   486.7    .045       0   506.1      .1       0
  551.62     .06       0  660.96    .055       0  770.29     .06       0
  789.01      .1       0
Bank Sta=486.7,506.1
XS Rating Curve= 0 ,0
Exp/Cntr(USF)=0,0
Exp/Cntr=0.3,0.1

Type RM Length L Ch R = 1 ,1354    ,305.8,305.8,305.8
XS GIS Cut Line= 2
2196312.26282833334248.4342338652196808.71792911334938.385197991
#Sta/Elev= 30
       0 1968.28    11.7 1964.02    26.9  1959.8      40 1957.01    55.1 1954.61
    72.3 1953.55  108.251949.516   149.2  1948.5   207.9 1948.99  252.161948.446
   302.7 1947.83   363.3 1948.03   379.5 1947.34   395.7 1947.41   399.7 1946.79
   405.3 1944.91   407.6 1944.38   415.9 1944.12   426.5 1944.83   440.1 1948.35
   448.2 1948.17  471.62 1949.25   476.5 1949.62  580.961950.366  690.291949.706
  697.041949.817   783.7 1951.49   803.9 1953.98   833.1 1959.64     850 1960.15
#Mann= 9 ,-1 , 0
       0      .1       0  108.25     .06       0  252.16    .055       0
   405.3    .045       0   426.5    .055       0  471.62    .035       0
  580.96    .055       0  690.29     .05       0  697.04     .06       0
#XS Ineff= 2 , 0
                          525.53         1953.32
Permanent Ineff=
       F       F
Bank Sta=405.3,426.5
XS Rating Curve= 0 ,0
Exp/Cntr(USF)=0,0
Exp/Cntr=0.3,0.1

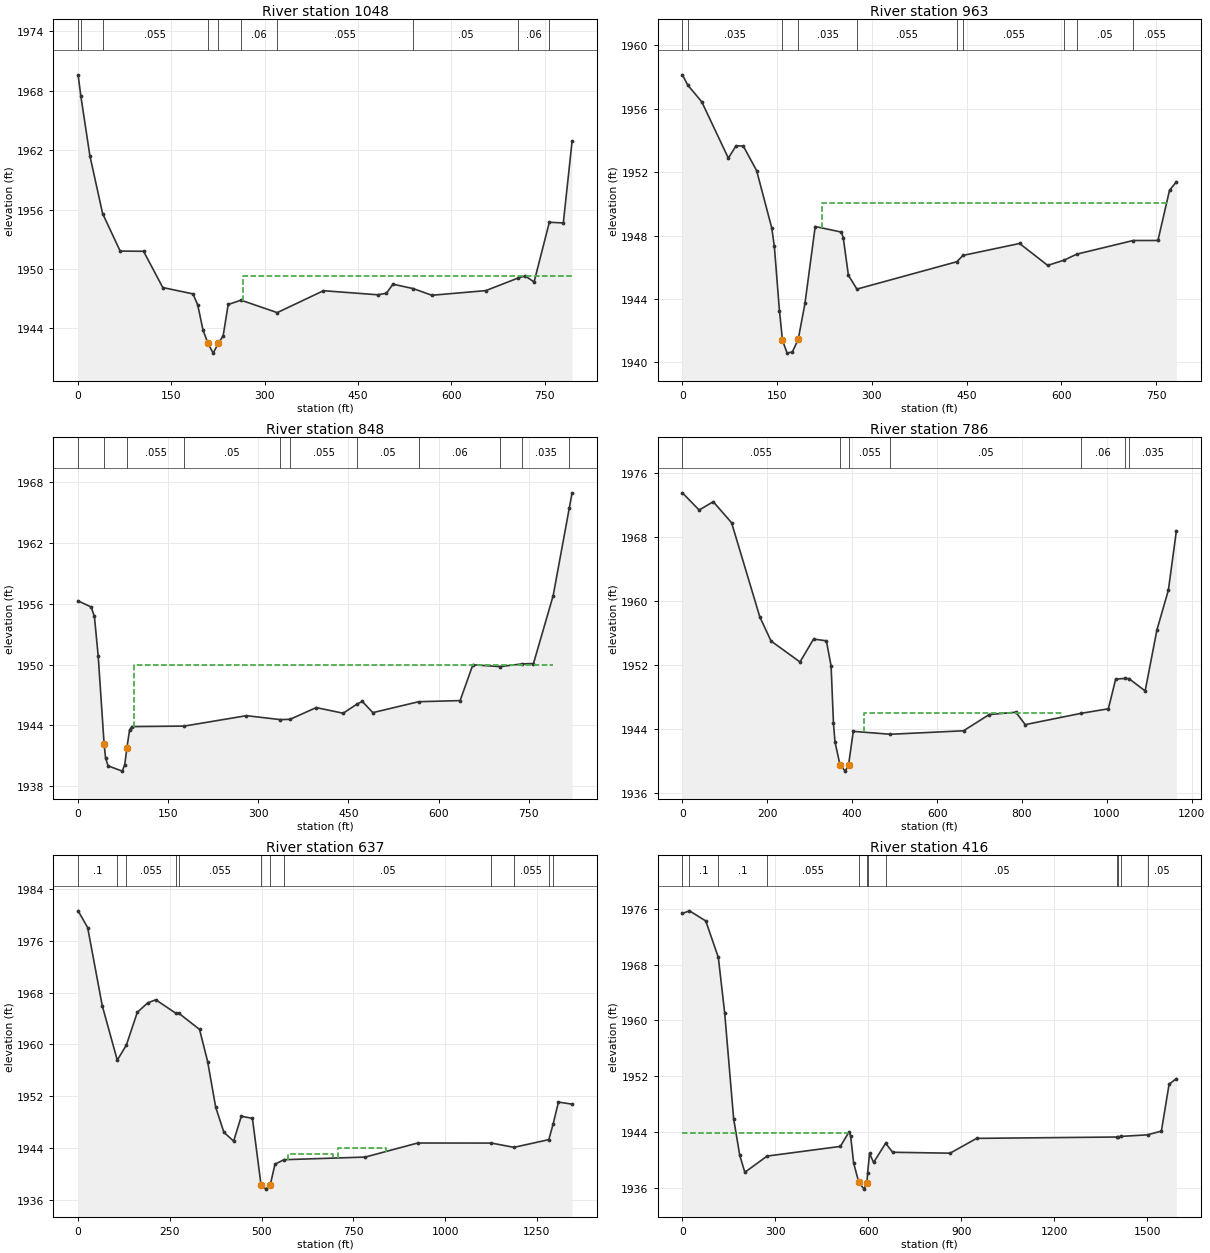
Type RM Length L Ch R = 1 ,1048    ,84.3,84.3,84.3
XS GIS Cut Line= 2
2196133.37461757334413.1512175942196597.06580128335057.568363762
#Sta/Elev= 30
       0  1969.6    4.341967.476    18.9 1961.44   39.36  1955.6    67.6 1951.81
   105.2 1951.79   136.1 1948.13   184.6 1947.49   192.2 1946.38   200.8 1943.82
   208.7  1942.5     217 1941.51   225.31942.487   233.1 1943.26   241.2 1946.42
   261.81946.855     3201945.598   394.3 1947.81   481.3  1947.4   495.4 1947.55
     506 1948.47  538.671948.022   568.6 1947.35   655.3 1947.82  706.681949.081
   718.7  1949.3   732.8 1948.69  757.34 1954.72   779.8 1954.65   793.9  1962.9
#Mann= 10 ,-1 , 0
       0    .055       0    4.34    .035       0   39.36    .055       0
   208.7    .045       0   225.3    .035       0   261.8     .06       0
     320    .055       0  538.67     .05       0  706.68     .06       0
  757.34      .1       0
#XS Ineff= 2 , 0
                          265.47         1949.26
Permanent Ineff=
       F       F
Bank Sta=208.7,225.3
XS Rating Curve= 0 ,0
Exp/Cntr(USF)=0,0
Exp/Cntr=0.5,0.3

Type RM Length L Ch R = 1 ,963     ,115.2,115.2,115.2
XS GIS Cut Line= 2
2196077.87415499334461.3351759162196534.56346125 335096.02142782
#Sta/Elev= 30
       0 1958.13    8.411957.487    30.6 1956.43    72.7 1952.88    84.9 1953.66
    96.4 1953.64   117.5 1952.09   141.4 1948.48   145.5 1947.32   153.6 1943.25
   158.4  1941.4   165.7 1940.59   174.1 1940.67   183.3 1941.46     194 1943.73
   210.2 1948.57   251.5 1948.22   254.6 1947.87   262.7  1945.5   276.21944.625
  434.491946.352  444.061946.748   533.7  1947.5   578.2 1946.12   604.2 1946.45
   624.21946.828  713.531947.688   752.7 1947.69     771 1950.85   781.9 1951.39
#Mann= 10 ,-1 , 0
       0    .055       0    8.41    .035       0   158.4    .045       0
   183.3    .035       0   276.2    .055       0  434.49     .06       0
  444.06    .055       0   604.2     .06       0   624.2     .05       0
  713.53    .055       0
#XS Ineff= 1 ,-1
   220.4  769.56 1950.03
Permanent Ineff=
       F
Bank Sta=158.4,183.3
XS Rating Curve= 0 ,0
Exp/Cntr(USF)=0,0
Exp/Cntr=0.5,0.3

Type RM Length L Ch R = 1 ,848     ,63.1,63.1,63.1
XS GIS Cut Line= 3
2196032.87117645334591.0783107452196379.30344266335090.009854864
2196579.50105776335168.325296132
#Sta/Elev= 30
       0 1956.29    21.6 1955.69    27.1 1954.76    33.4 1950.88    43.31942.134
    45.7 1940.77    49.9 1939.99    73.5 1939.47    77.7 1940.12    81.1 1941.73
    85.7 1943.54    89.7 1943.87  176.56 1943.92   280.3 1944.95  336.72 1944.56
  352.931944.591   396.4 1945.75   441.3 1945.19  464.341946.099   473.1 1946.36
   490.7 1945.25  566.941946.329     636 1946.44   657.2 1949.98  702.511949.798
  739.261950.068   758.1  1950.1   790.9 1956.81  817.881965.513   822.4 1966.97
#Mann= 11 ,-1 , 0
       0    .055       0    43.3    .045       0    81.1    .055       0
  176.56     .05       0  336.72     .06       0  352.93    .055       0
  464.34     .05       0  566.94     .06       0  702.51    .055       0
  739.26    .035       0  817.88     .06       0
#XS Ineff= 1 ,-1
   93.09  789.79 1949.99
Permanent Ineff=
       F
Bank Sta=43.3,81.1
XS Rating Curve= 0 ,0
Exp/Cntr(USF)=0,0
Exp/Cntr=0.5,0.3

Type RM Length L Ch R = 1 ,786     ,148.7,148.5,149.6
XS GIS Cut Line= 4
2195939.99076618334314.1435177912195993.96487202334645.590993154
2196315.58949899335093.4069428972196577.26652235335183.440825163
#Sta/Elev= 30
       0 1973.49    39.4 1971.34    72.7 1972.38   115.9 1969.75   182.4 1957.98
   208.9 1954.97     277 1952.36     309 1955.22   339.2    1955   350.3 1951.87
   355.9 1944.71   359.4  1942.4   371.11939.542   383.6 1938.72   391.41939.482
   402.6 1943.69  489.971943.326   662.3 1943.76   722.9 1945.79   785.8 1946.08
   807.7 1944.53  939.33 1945.94  1003.6 1946.51  1020.9 1950.22 1043.06  1950.3
 1052.04 1950.28  1090.3 1948.74    1118 1956.35    1145 1961.33  1163.9 1968.75
#Mann= 7 ,-1 , 0
       0    .055       0   371.1    .045       0   391.4    .055       0
  489.97     .05       0  939.33     .06       0 1043.06    .055       0
 1052.04    .035       0
#XS Ineff= 1 ,-1
  428.59  892.95    1946
Permanent Ineff=
       F
Bank Sta=371.1,391.4
XS Rating Curve= 0 ,0
Exp/Cntr(USF)=0,0
Exp/Cntr=0.3,0.1

Type RM Length L Ch R = 1 ,637     ,220.9,221,218.2
XS GIS Cut Line= 4
2195574.08129852334402.681485287 2195888.4919641 334751.06390107
2196192.22624973 335176.746858042196537.36567129335254.844484452
#Sta/Elev= 30
       0 1980.62      26 1978.04    65.7 1965.99   106.71957.559   131.51959.892
   161.3 1964.95   189.5  1966.4   211.6 1966.89  266.841964.785  273.961964.828
   330.9 1962.31     353 1957.34   374.9  1950.3   397.2 1946.43   423.8 1945.06
   444.7  1948.9     475 1948.58   498.5  1938.3   512.3 1937.65   523.81938.351
   536.5  1941.5  560.751942.192   782.4  1942.6   925.3 1944.77  1126.31944.763
 1187.481944.102 1282.731945.289 1294.591947.732  1308.9 1951.09  1346.1 1950.77
#Mann= 12 ,-1 , 0
       0      .1       0   106.7      .1       0   131.5    .055       0
  266.84      .1       0  273.96    .055       0   498.5    .045       0
   523.8    .055       0  560.75     .05       0  1126.3     .06       0
 1187.48    .055       0 1282.73     .05       0 1294.59    .035       0
#XS Ineff= 2 ,-1
  572.07  695.18 1943.05  706.84  837.97 1943.95
Permanent Ineff=
       F       F
Bank Sta=498.5,523.8
XS Rating Curve= 0 ,0
Exp/Cntr(USF)=0,0
Exp/Cntr=0.3,0.1

Type RM Length L Ch R = 1 ,416     ,293.2,293.2,293.2
XS GIS Cut Line= 4
2195351.84395384 334531.847493762195736.29055268334913.946113295
2196123.73561459335349.775831025  2196592.172436335349.077845167
#Sta/Elev= 30
       0 1975.33   22.821975.702    75.4 1974.25  115.871969.023   136.4 1961.05
   165.2 1945.94   185.1 1940.66   201.4 1938.25  273.051940.572   509.6 1941.96
   537.8 1944.06   542.6 1943.46   552.5 1939.56   569.11936.794   586.1 1935.84
   595.41936.787  597.591938.202   603.7 1940.95   616.8 1939.66  655.531942.407
   678.3 1941.12   863.6 1940.99   949.1 1943.11  1402.61943.305 1405.141943.312
 1414.14 1943.39 1500.441943.617  1545.2 1944.15  1570.1 1950.88  1593.6 1951.66
#Mann= 12 ,-1 , 0
       0     .06       0   22.82      .1       0  115.87      .1       0
  273.05    .055       0   569.1    .045       0   595.4    .055       0
  597.59      .1       0  655.53     .05       0  1402.6     .06       0
 1405.14     .05       0 1414.14    .055       0 1500.44     .05       0
#XS Ineff= 2 , 0
           534.3 1943.91   653.3         1942.22
Permanent Ineff=
       F       F
Bank Sta=569.1,595.4
XS Rating Curve= 0 ,0
Exp/Cntr(USF)=0,0
Exp/Cntr=0.3,0.1

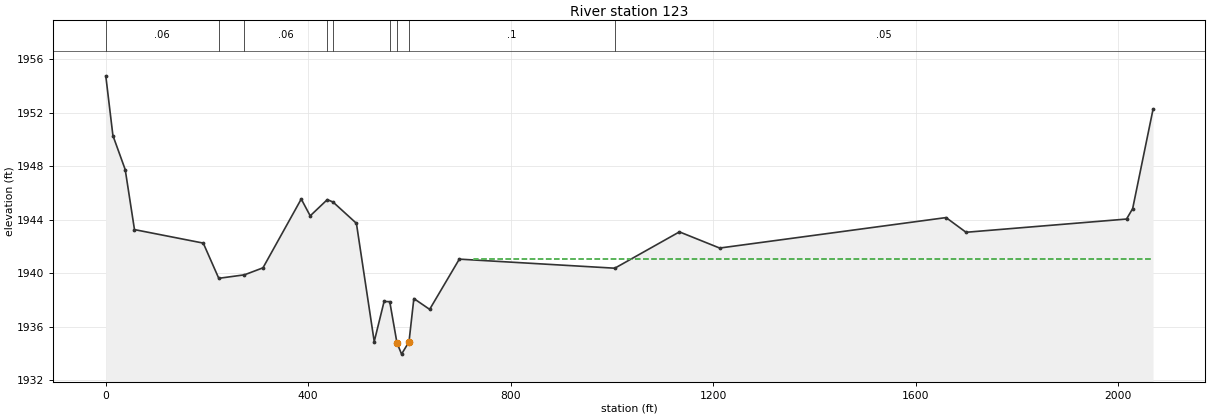
Type RM Length L Ch R = 1 ,123     ,124,124,124
XS GIS Cut Line= 4
2195109.21847931 334713.052910752195473.27583294335026.094521712
2195745.79316521335446.6609528862196830.05238797335536.280914469
#Sta/Elev= 30
       0 1954.77    14.1  1950.3    38.4 1947.75    56.7 1943.26   192.6 1942.25
  223.241939.615  273.981939.875   310.6  1940.4   386.2 1945.55   403.9 1944.29
  437.731945.505  449.081945.321   495.2 1943.73   530.4 1934.88   549.9 1937.88
  561.071937.866   575.3 1934.79   584.4 1933.94   599.1 1934.86   608.7  1938.1
   639.9 1937.29   698.5 1941.05 1005.721940.371  1133.4 1943.09  1212.9 1941.88
  1660.2 1944.16  1699.7 1943.06  2016.8 1944.05  2028.9 1944.83  2069.2 1952.27
#Mann= 9 ,-1 , 0
       0     .06       0  223.24      .1       0  273.98     .06       0
  437.73    .035       0  449.08    .055       0  561.07      .1       0
   575.3    .045       0   599.1      .1       0 1005.72     .05       0
#XS Ineff= 2 , 0
          438.25 1945.24  726.79         1941.07
Permanent Ineff=
       F       F
Bank Sta=575.3,599.1
XS Rating Curve= 0 ,0
Exp/Cntr(USF)=0,0
Exp/Cntr=0.3,0.1
LCMann Table=0

Chan Stop Cuts=-1
Use User Specified Reach Order=0
Composite Channel Slope=5